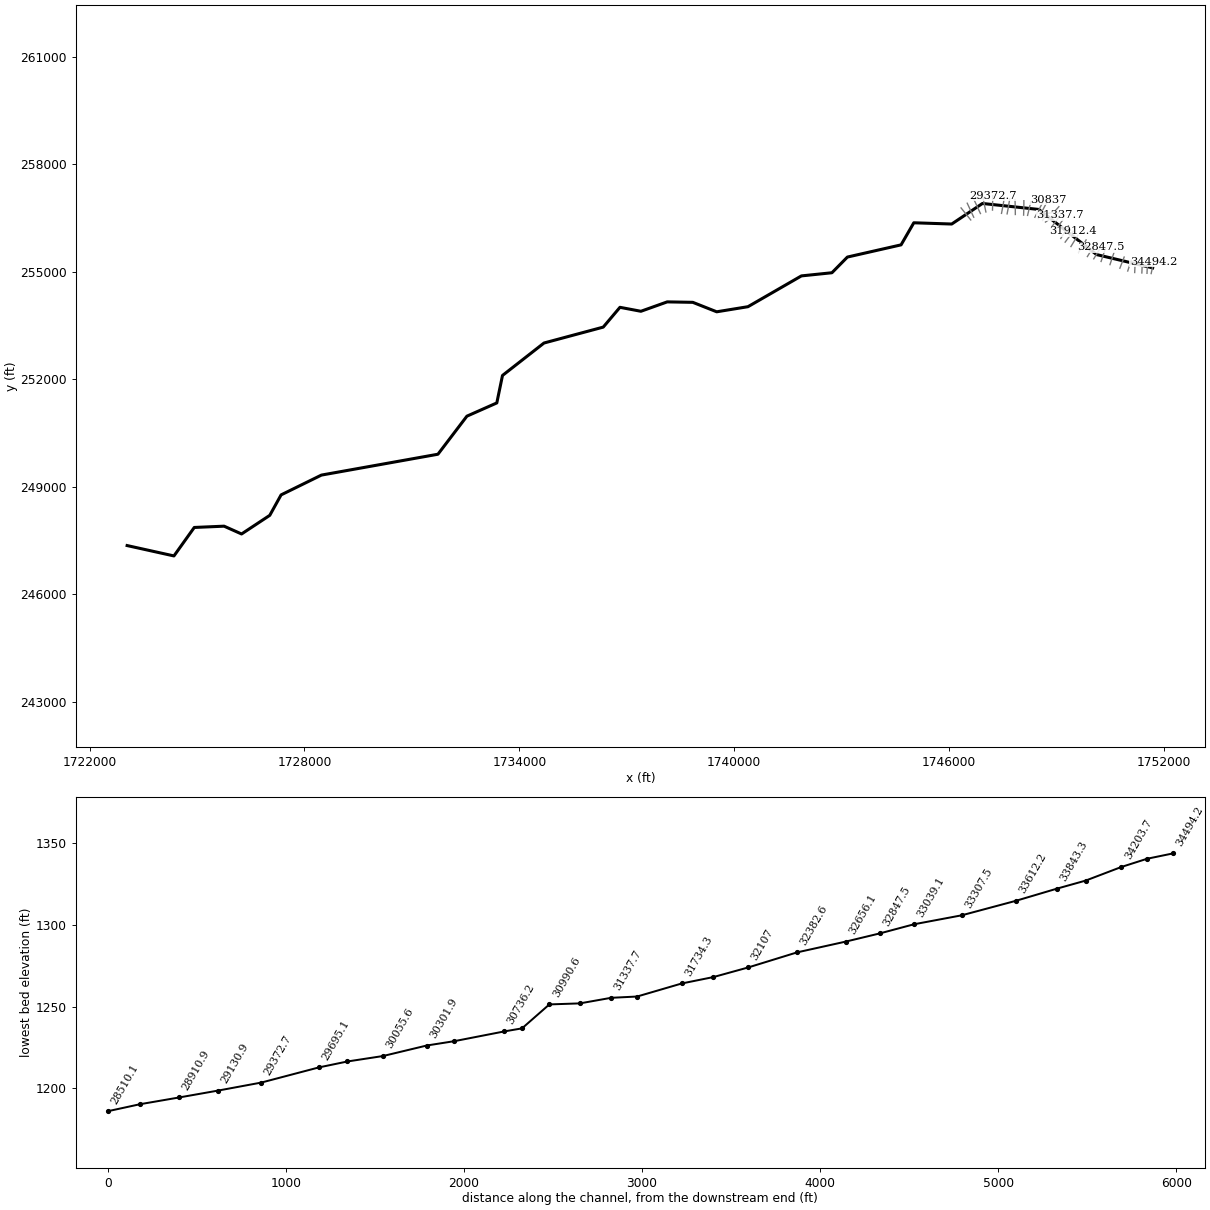
--- ELKCRK.prj (project) ---

Proj Title=ELKCRK
Current Plan=p01
Default Exp/Contr=0,0
English Units
Geom File=g01
Flow File=f01
Plan File=p01
BEGIN DESCRIPTION:
END DESCRIPTION:
DSS Export Rating Curves= 0
DSS Export Rating Curve Sorted= 0
DSS Export Volume Flow Curves= 0
DXF OffsetX= 0
DXF OffsetY= 0
DXF ScaleX= 0
DXF ScaleY= 0

--- ELKCRK.p01 (plan) ---

Plan Title=Floodplain
Program Version=4.00
Geom File=g01
Flow File=f01
K Sum by GR=0
Std Step Tol=0.01
Critical Tol=0.01
Num of Std Step Trials=20
Max Error Tol=0.3
Flow Tol Ratio=0.001
Split Flow NTrial=30
Split Flow Tol=0.02
Split Flow Ratio=0.02
Log Output Level=0
Friction Slope Method=1
Unsteady Friction Slope Method=2
Unsteady Bridges Friction Slope Method=1
Global Log Level=0
CheckData=False
Run HTab=0
Run UNet=0
Run PostProcess=0
UNET Theta=0
UNET Theta Warmup=0
UNET ZTol=0
UNET ZSATol=0
UNET MxIter=0
UNET MaxInSteps=0
UNET DtIC=0
UNET DtMin=0
UNET MaxCRTS=0
UNET WFStab=0
UNET SFStab=0
UNET WFX=0
UNET SFX=0
UNET DSS MLevel=0
UNET DZMax Abort=0
UNET Convert EG Bridges=0
UNET Use Existing IB Tables=0
UNET Froude Limit=0
UNET Froude Power=0
Write IC File=0
Echo Input=False
Echo Output=False
Write Detailed=0

--- ELKCRK.f01 (steady flow) ---

Flow Title=NFF Regression Equation
Program Version=4.00
Number of Profiles=1
Profile Names=P100yr
River Rch & RM=ELKCRK,Main      ,34494.2
918.3981
River Rch & RM=ELKCRK,Main      ,32656.1
967.8691
River Rch & RM=ELKCRK,Main      ,30990.6
1074.293
River Rch & RM=ELKCRK,Main      ,30457
1381.834
River Rch & RM=ELKCRK,Main      ,29695.1
1469.995
River Rch & RM=ELKCRK,Main      ,26248.6
1598.783
River Rch & RM=ELKCRK,Main      ,21811.5
1759.509
River Rch & RM=ELKCRK,Main      ,18451.2
1954.539
River Rch & RM=ELKCRK,Main      ,13720.3
2130.766
River Rch & RM=ELKCRK,Main      ,13300.7
2699.825
River Rch & RM=ELKCRK,Main      ,10309.7
2815.858
River Rch & RM=ELKCRK,Main      ,9848.3
3220.453
River Rch & RM=ELKCRK,Main      ,9532.6
3225.271
River Rch & RM=ELKCRK,Main      ,184.4
3580.431
Boundary for River Rch & Prof#=ELKCRK,Main      ,1
Up Type=0
Dn Type=3
Dn Slope=0.007305

--- ELKCRK.g01 (geometry) ---

Geom Title=USGS 10m DEM
Program Version=4.10

River Reach=ELKCRK          ,Main
Reach XY= 30
     1751684.181      255109.473     1750118.291      255481.256
     1748503.986      256740.721     1746931.999      256907.504
     1746073.845      256333.693     1745015.247      256368.439
     1744659.679      255752.275     1743160.964      255411.763
     1742728.955      254973.963     1741876.972      254886.062
     1740384.751      254026.553     1739511.466      253884.094
     1738844.341      254148.164      1738129.73      254160.904
     1737395.427      253898.523     1736810.537       254009.18
     1736343.781      253456.717     1734689.867      253013.125
     1733530.505       252107.41     1733371.831       251340.68
     1732536.767      250971.213     1731728.341      249909.141
      1728474.37      249326.854     1727348.596      248774.391
     1727032.407      248203.397     1726244.829      247683.364
     1725757.225      247901.106     1724924.477      247865.201
     1724356.958      247070.674     1723049.346      247360.225

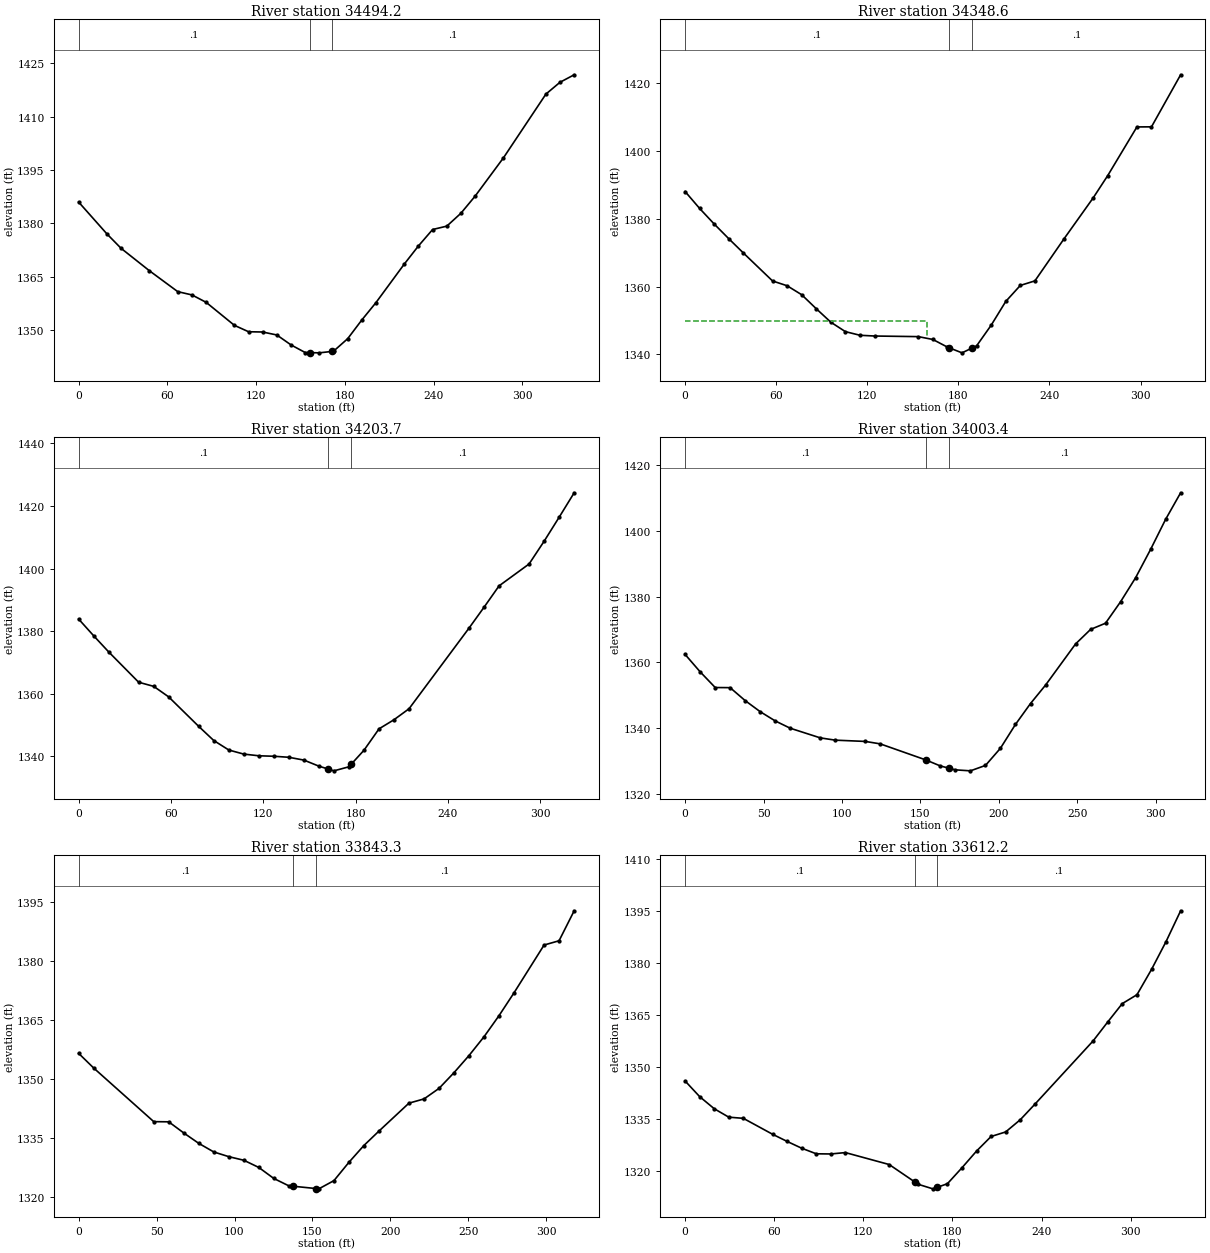
Type RM Length L Ch R = 1 ,34494.2 ,141.8,145.6,149.3
XS GIS Cut Line= 2
     1751642.601      254950.619     1751711.998      255278.372
#Sta/Elev= 30
       0 1386.01    19.1 1377.08    28.7 1373.02    47.9 1366.71      67 1360.86
    76.6 1359.94    86.2 1357.86   105.3  1351.4   114.9  1349.6   124.4 1349.53
     134 1348.69   143.6  1345.9   153.2 1343.76   156.1 1343.74   162.7 1343.68
   171.1 1344.07   172.3 1344.13   181.9 1347.66   191.4 1352.88     201 1357.78
   220.2 1368.63   229.7 1373.68   239.3  1378.3   248.9 1379.25   258.4 1382.85
     268 1387.65   287.2 1398.43   315.9 1416.32   325.4 1419.63     335 1421.74
#Mann= 3 , 0 , 0
       0      .1       0   156.1    .045       0   171.1      .1       0
Bank Sta=156.1,171.1
XS Rating Curve= 0 ,0
Exp/Cntr=0.3,0.1

Type RM Length L Ch R = 1 ,34348.6 ,144.9,144.9,144.9
XS GIS Cut Line= 2
     1751526.526      254958.074     1751541.292      255284.126
#Sta/Elev= 30
       0 1388.08     9.6 1383.06    19.2 1378.46    28.8 1374.12    38.4 1369.91
    57.6 1361.65    67.2 1360.23    76.8 1357.58    86.4 1353.44      96 1349.46
   105.6 1346.67   115.2  1345.6   124.8 1345.38   153.6  1345.2   163.2 1344.36
   172.8  1342.1   174.1 1341.87   182.4 1340.41   189.1 1341.85     192 1342.47
   201.6 1348.57   211.2 1355.59   220.8 1360.33   230.4 1361.67   249.6 1374.11
   268.8  1386.2   278.4  1392.8   297.6 1407.16   307.2 1407.19   326.4 1422.57
#Mann= 3 , 0 , 0
       0      .1       0   174.1    .045       0   189.1      .1       0
#XS Ineff= 2 , 0
          159.65 1349.77
Permanent Ineff=
       F       F
Bank Sta=174.1,189.1
XS Rating Curve= 0 ,0
Exp/Cntr=0.3,0.1

Type RM Length L Ch R = 1 ,34203.7 ,200.3,200.3,200.3
XS GIS Cut Line= 2
      1751382.36      254967.332     1751396.928      255288.992
#Sta/Elev= 30
       0 1383.86     9.8 1378.51    19.5 1373.38      39 1363.68    48.8 1362.36
    58.5    1359    78.1 1349.54    87.8 1345.06    97.6 1342.02   107.3 1340.72
   117.1 1340.18   126.8 1340.03   136.6  1339.7   146.4  1338.8   156.1 1336.87
   162.1 1335.95   165.9 1335.37   175.6 1336.66   177.1 1337.47   185.4 1341.94
   195.2 1348.79   204.9 1351.69   214.7 1355.21   253.7 1380.99   263.4 1387.62
   273.2 1394.47   292.7 1401.46   302.5 1408.75   312.2 1416.37     322 1424.21
#Mann= 3 , 0 , 0
       0      .1       0   162.1    .045       0   177.1      .1       0
Bank Sta=162.1,177.1
XS Rating Curve= 0 ,0
Exp/Cntr=0.3,0.1

Type RM Length L Ch R = 1 ,34003.4 ,166.3,160,153.7
XS GIS Cut Line= 2
     1751182.736      254980.152     1751197.028      255295.731
#Sta/Elev= 30
       0 1362.44     9.6 1357.15    19.2 1352.38    28.7 1352.34    38.3  1348.4
    47.9 1345.03    57.4 1342.24      67 1340.01    86.2 1337.07    95.7 1336.38
   114.9 1335.99   124.4 1335.25   153.5 1330.36   162.7 1328.54   168.5 1327.82
   172.3 1327.35   181.9 1327.05   191.5  1328.7     201  1333.9   210.6 1341.16
   220.2 1347.52   229.8 1353.13   248.9 1365.62   258.5 1370.05     268 1371.93
   277.6 1378.45   287.2 1385.77   296.8 1394.42   306.3 1403.49   315.9 1411.59
#Mann= 3 , 0 , 0
       0      .1       0   153.5    .045       0   168.5      .1       0
Bank Sta=153.5,168.5
XS Rating Curve= 0 ,0
Exp/Cntr=0.3,0.1

Type RM Length L Ch R = 1 ,33843.3 ,233.4,231.1,233.1
XS GIS Cut Line= 2
     1750988.096       255022.26     1751088.182      255323.964
#Sta/Elev= 30
       0  1356.6     9.6 1352.89    48.2 1339.24    57.8  1339.2    67.4 1336.38
    77.1 1333.72    86.7 1331.54    96.3 1330.35     106 1329.43   115.6  1327.6
   125.2 1324.81   134.8 1322.94   137.4 1322.84   152.4 1322.24   154.1 1322.17
   163.8 1324.26   173.4 1328.91     183 1333.18   192.6 1336.82   211.9 1343.94
   221.6 1345.02   231.2 1347.69   240.8 1351.68   250.4 1356.02   260.1 1360.83
   269.7 1366.18   279.3 1371.97   298.6 1384.12   308.2  1385.2   317.9 1392.82
#Mann= 3 , 0 , 0
       0      .1       0   137.4    .045       0   152.4      .1       0
Bank Sta=137.4,152.4
XS Rating Curve= 0 ,0
Exp/Cntr=0.3,0.1

Type RM Length L Ch R = 1 ,33612.2 ,303.3,304.4,305.4
XS GIS Cut Line= 2
     1750769.019      255100.797      1750889.01      255412.059
#Sta/Elev= 30
       0 1345.86     9.8 1341.34    19.6 1337.85    29.4 1335.41    39.2 1335.07
    58.9 1330.47    68.7  1328.4    78.5 1326.44    88.3 1324.83    98.1 1324.78
   107.9 1325.18   137.4 1321.73   154.8 1316.65     157 1316.01   166.8 1314.71
   169.8 1315.16   176.6 1316.19   186.4  1320.8   196.2 1325.62     206 1329.83
   215.8 1331.14   225.7 1334.69   235.5 1339.16   274.7 1357.44   284.5 1362.89
   294.3  1368.2   304.2 1370.77     314 1378.07   323.8 1386.13   333.6 1395.01
#Mann= 3 , 0 , 0
       0      .1       0   154.8    .045       0   169.8      .1       0
Bank Sta=154.8,169.8
XS Rating Curve= 0 ,0
Exp/Cntr=0.3,0.1

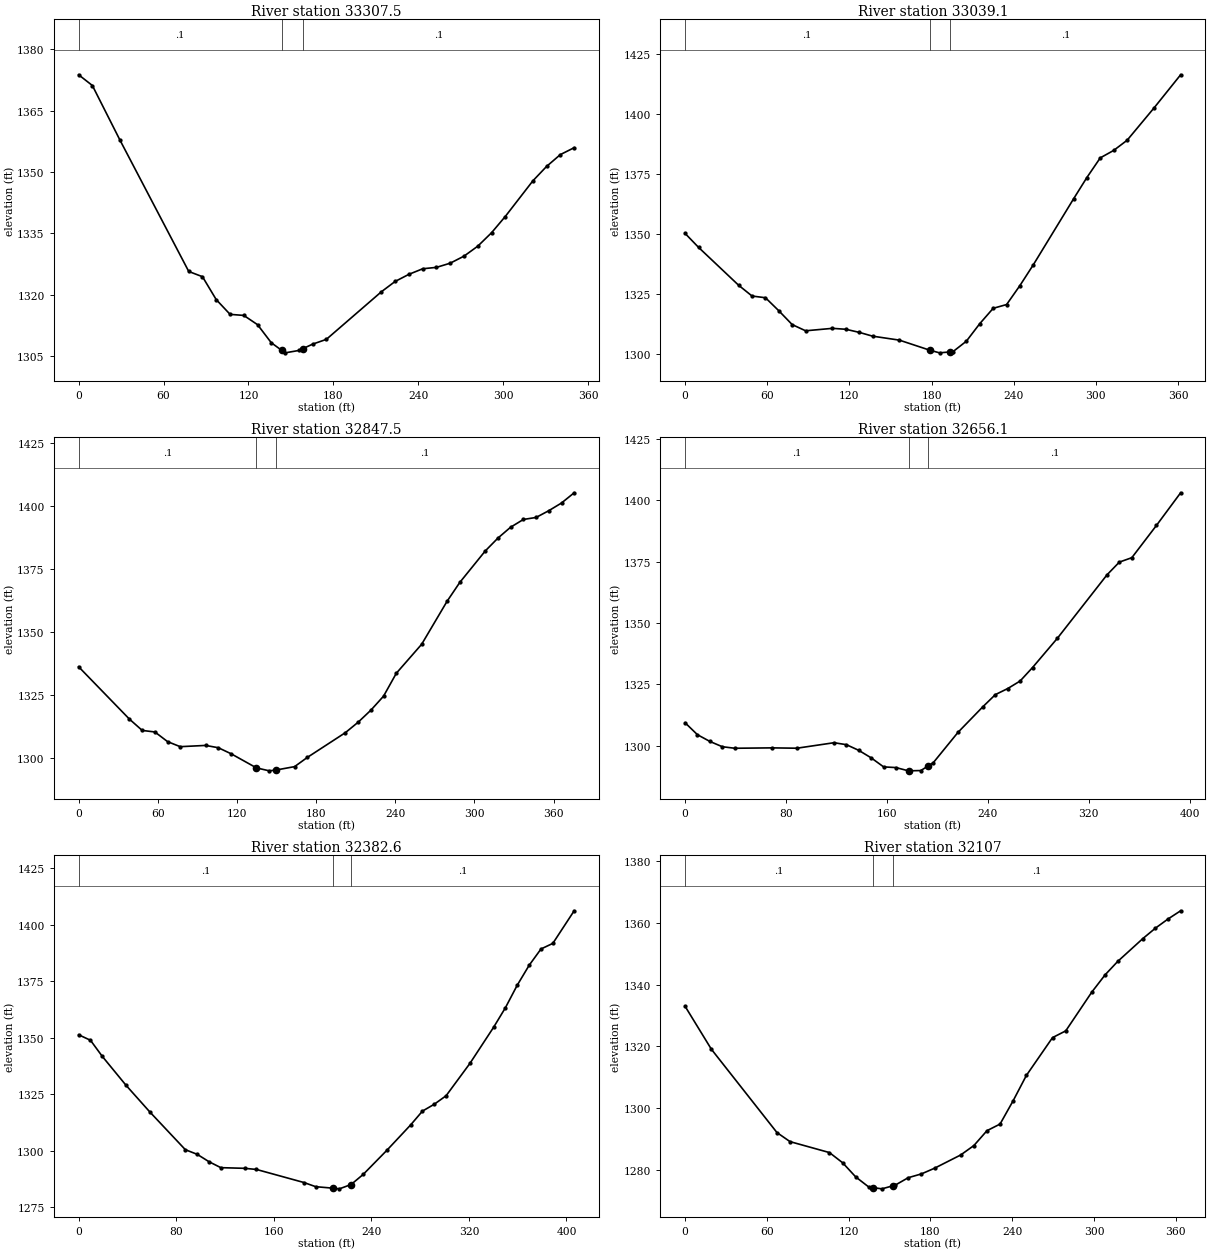
Type RM Length L Ch R = 1 ,33307.5 ,268.3,268.3,268.3
XS GIS Cut Line= 2
     1750492.555      255199.907     1750602.777      255532.161
#Sta/Elev= 30
       0 1373.77     9.7 1371.15    29.2 1357.81    77.8 1325.72    87.5 1324.44
    97.2 1318.85     107 1315.24   116.7 1314.98   126.4 1312.72   136.1 1308.31
   143.5 1306.44   145.9 1305.84   155.6 1306.42   158.5 1306.88   165.3 1307.96
     175 1309.13   213.9 1320.76   223.6 1323.28   233.4 1325.03   243.1 1326.38
   252.8 1326.72   262.5 1327.74   272.3 1329.47     282  1331.9   291.7 1335.17
   301.4 1339.14   320.9 1347.85   330.6 1351.38   340.3 1354.26   350.1 1355.96
#Mann= 3 , 0 , 0
       0      .1       0   143.5    .045       0   158.5      .1       0
Bank Sta=143.5,158.5
XS Rating Curve= 0 ,0
Exp/Cntr=0.3,0.1

Type RM Length L Ch R = 1 ,33039.1 ,196.8,191.5,186
XS GIS Cut Line= 2
     1750244.541      255288.818     1750358.493      255632.317
#Sta/Elev= 30
       0 1350.18     9.8 1344.37    39.1 1328.55    48.9 1324.05    58.7 1323.34
    68.5 1317.87    78.2 1312.14      88 1309.55   107.6 1310.57   117.4 1310.18
   127.2 1308.89   136.9 1307.31   156.5 1305.65   178.5 1301.49   185.8 1300.35
   193.5 1300.73   195.6 1300.83   205.4  1305.2   215.2 1312.52     225 1318.93
   234.8  1320.5   244.5  1328.4   254.3 1337.08   283.7  1364.6   293.4 1373.48
   303.2  1381.7     313 1384.81   322.8 1389.04   342.4 1402.49   361.9 1416.37
#Mann= 3 , 0 , 0
       0      .1       0   178.5    .045       0   193.5      .1       0
Bank Sta=178.5,193.5
XS Rating Curve= 0 ,0
Exp/Cntr=0.3,0.1

Type RM Length L Ch R = 1 ,32847.5 ,191.4,191.4,191.6
XS GIS Cut Line= 2
     1750039.384      255362.364     1750235.238      255682.852
#Sta/Elev= 30
       0 1336.09    38.5 1315.31    48.2 1310.82    57.8 1310.21    67.4 1306.38
      77 1304.37    96.3 1304.87   105.9 1303.95   115.6 1301.55   134.8 1295.95
   144.5 1294.78   149.8 1295.12   163.7 1296.45   173.4 1300.13   202.2 1309.94
   211.9  1314.1   221.5 1318.85   231.1 1324.41   240.8 1333.52     260 1345.02
   279.3 1362.12   288.9 1369.57   308.2 1382.06   317.8 1387.17   327.4 1391.48
   337.1 1394.57   346.7 1395.36   356.3 1398.03     366  1401.1   375.6 1405.16
#Mann= 3 , 0 , 0
       0      .1       0   134.8    .045       0   149.8      .1       0
Bank Sta=134.8,149.8
XS Rating Curve= 0 ,0
Exp/Cntr=0.3,0.1

Type RM Length L Ch R = 1 ,32656.1 ,273.4,273.4,273.4
XS GIS Cut Line= 3
     1749861.817       255426.02     1750051.636      255736.631
     1750066.042      255761.698
#Sta/Elev= 30
       0 1309.36     9.8 1304.49    19.7 1301.74    29.5  1299.6    39.4 1298.97
    68.9 1299.13    88.6 1298.99   118.1 1301.23   127.9 1300.43   137.7 1298.12
   147.6 1295.04   157.4 1291.38   167.2  1291.1   177.1 1289.77   177.8 1289.78
   186.9 1289.89   192.8  1291.8   196.8  1293.1   216.4 1305.47   236.1 1315.89
     246 1320.83   255.8  1323.3   265.6 1326.36   275.5 1331.88   295.2 1343.81
   334.5 1369.63   344.3 1374.83   354.2 1376.63   373.7 1389.76   392.9 1403.08
#Mann= 3 , 0 , 0
       0      .1       0   177.8    .045       0   192.8      .1       0
Bank Sta=177.8,192.8
XS Rating Curve= 0 ,0
Exp/Cntr=0.3,0.1

Type RM Length L Ch R = 1 ,32382.6 ,274.9,274.7,274.4
XS GIS Cut Line= 3
      1749614.69       255543.05     1749817.423      255874.793
     1749826.165      255890.004
#Sta/Elev= 30
       0 1351.36     9.7 1348.93    19.4  1341.8    38.9 1328.98    58.3 1317.25
    87.5  1300.5    97.2 1298.46   106.9 1295.18   116.6 1292.55   136.1 1292.26
   145.8 1291.76   184.7 1285.98   194.4 1284.13   208.4 1283.48   213.8 1283.18
   223.4  1285.1   233.3 1289.55   252.7 1300.22   272.2 1311.45   281.9 1317.58
   291.6 1320.62   301.3 1324.38   320.8 1338.67   340.2 1354.64   349.9  1363.3
   359.6 1373.28   369.4 1382.12   379.1 1389.33   388.8  1391.8   406.3 1406.23
#Mann= 3 , 0 , 0
       0      .1       0   208.4    .045       0   223.4      .1       0
Bank Sta=208.4,223.4
XS Rating Curve= 0 ,0
Exp/Cntr=0.3,0.1

Type RM Length L Ch R = 1 ,32107   ,196.9,194.8,192.7
XS GIS Cut Line= 3
      1749402.15      255705.112     1749562.846      255968.067
     1749590.443      256016.088
#Sta/Elev= 30
       0 1332.98    19.3 1319.09    67.4 1292.15      77 1289.22   105.9 1285.68
   115.6 1282.38   125.2  1277.8   134.8 1274.53   137.6 1274.36   144.4 1273.95
   152.6 1274.95   154.1 1275.13   163.7 1277.55   173.4 1278.78     183 1280.61
   202.2  1284.9   211.9 1287.95   221.5 1292.76   231.1  1294.9   240.8 1302.52
   250.4 1310.62   269.6 1322.86   279.3 1325.04   298.5 1337.63   308.2 1343.17
   317.4 1347.49   335.9  1354.9   345.1 1358.26   354.3 1361.21   363.6 1363.88
#Mann= 3 , 0 , 0
       0      .1       0   137.6    .045       0   152.6      .1       0
Bank Sta=137.6,152.6
XS Rating Curve= 0 ,0
Exp/Cntr=0.3,0.1

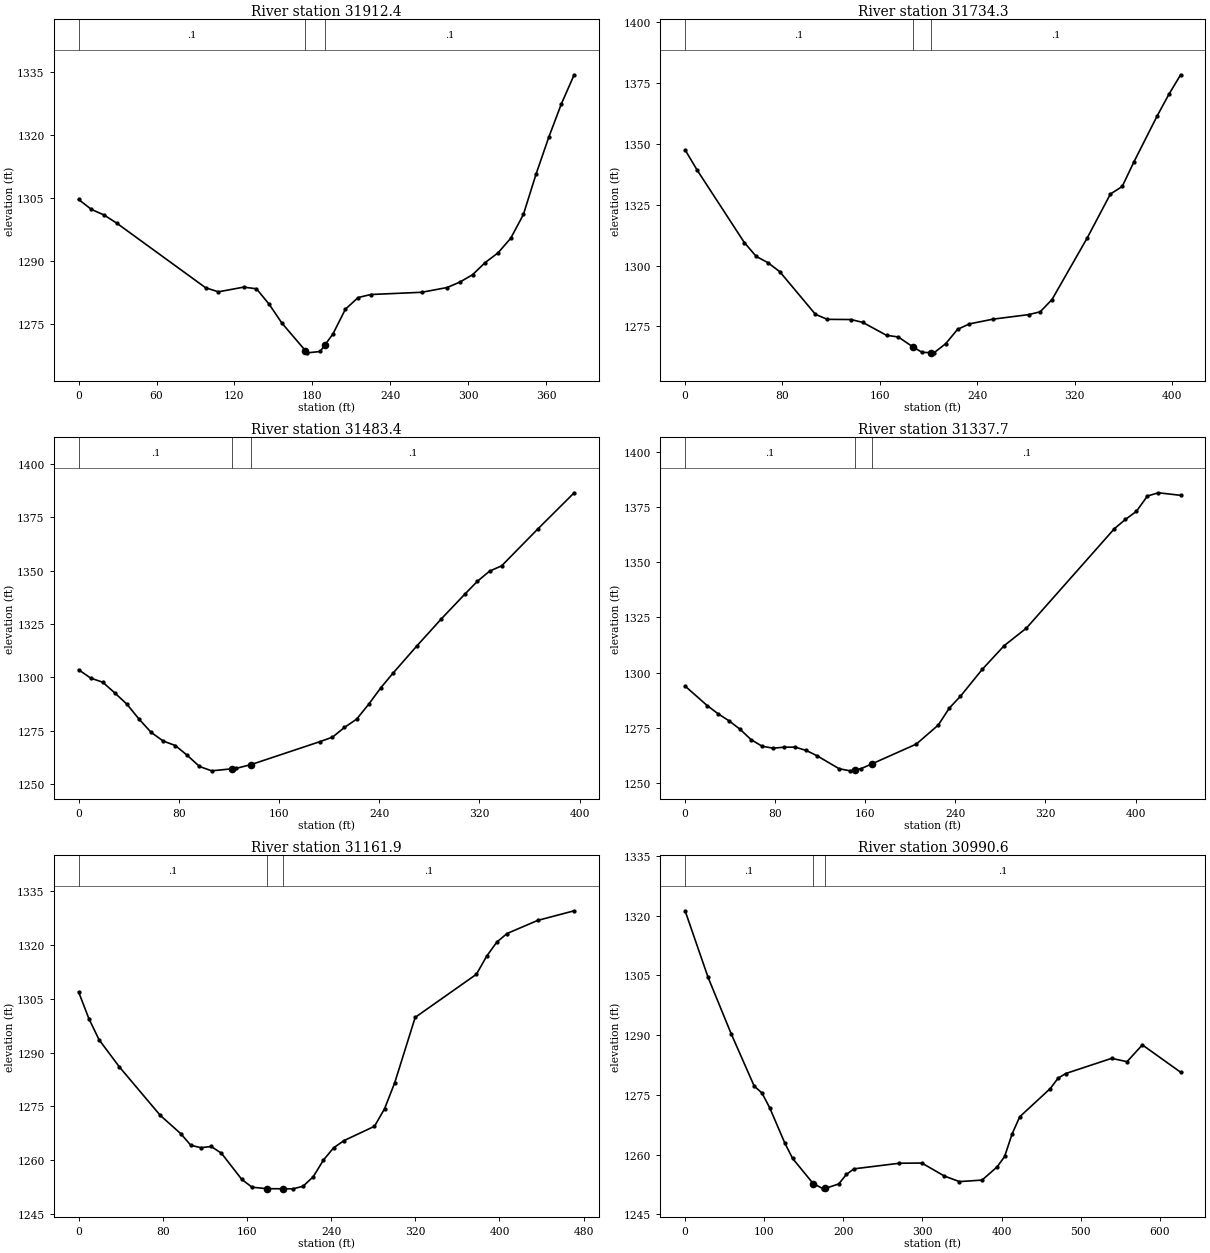
Type RM Length L Ch R = 1 ,31912.4 ,175.5,177.6,179.7
XS GIS Cut Line= 2
     1749240.682      255828.231     1749468.751      256134.309
#Sta/Elev= 30
       0 1304.61     9.8 1302.25    19.6 1300.91    29.4 1298.96    97.9 1283.57
   107.7 1282.62   127.2 1283.74     137 1283.34   146.8 1279.64   156.6 1275.16
   174.7 1268.61   176.2 1268.09     186 1268.41   189.7 1269.97   195.8 1272.54
   205.5 1278.49   215.3 1281.26   225.1 1281.98   264.3 1282.51   283.8 1283.64
   293.6 1284.93   303.4 1286.68   313.2  1289.6     323 1291.88   332.8 1295.36
   342.6 1301.04   352.3 1310.61   362.1  1319.4   371.9 1327.42   381.7  1334.3
#Mann= 3 , 0 , 0
       0      .1       0   174.7    .045       0   189.7      .1       0
Bank Sta=174.7,189.7
XS Rating Curve= 0 ,0
Exp/Cntr=0.3,0.1

Type RM Length L Ch R = 1 ,31734.3 ,252.9,251,249.2
XS GIS Cut Line= 3
     1749119.764      255931.272     1749261.919      256163.889
     1749328.999      256280.612
#Sta/Elev= 30
       0 1347.44     9.7  1339.3    48.7  1309.4    58.4 1303.75    68.2 1301.12
    77.9 1297.41   107.1 1279.98   116.8 1277.92   136.3 1277.84     146 1276.67
   165.5 1271.37   175.2 1270.69   187.4 1266.54   194.7  1264.4   202.4 1264.23
   204.5 1264.18   214.2 1267.96   223.9 1273.82   233.7 1276.06   253.1    1278
   282.2 1279.85   291.8 1281.01   301.5 1286.05   330.3 1311.19   349.5 1329.33
   359.2 1332.43   368.8  1342.5     388 1361.44   397.6 1370.28   407.2 1378.24
#Mann= 3 , 0 , 0
       0      .1       0   187.4    .045       0   202.4      .1       0
Bank Sta=187.4,202.4
XS Rating Curve= 0 ,0
Exp/Cntr=0.3,0.1

Type RM Length L Ch R = 1 ,31483.4 ,145.9,145.6,145.3
XS GIS Cut Line= 2
     1748936.943      256126.281     1749173.353      256443.554
#Sta/Elev= 30
       0 1303.58     9.6 1299.67    19.3  1297.7      29 1292.65    38.6  1287.4
    48.2 1280.46    57.9 1274.22    67.6 1270.14    77.2 1268.06    86.8 1263.43
    96.5 1258.24   106.2 1256.19   122.7 1257.16   125.5  1257.3   137.7 1259.12
     193 1269.94   202.7 1271.98   212.3 1276.54     222 1280.42   231.6  1287.4
   241.3 1295.11   250.9 1301.88   270.2 1314.81   289.5 1327.34   308.8 1339.25
   318.5 1345.07   328.1 1349.77   337.8 1352.29   366.7 1369.57   395.7 1386.52
#Mann= 3 , 0 , 0
       0      .1       0   122.7    .045       0   137.7      .1       0
Bank Sta=122.7,137.7
XS Rating Curve= 0 ,0
Exp/Cntr=0.3,0.1

Type RM Length L Ch R = 1 ,31337.7 ,182.6,175.6,168.7
XS GIS Cut Line= 3
     1748844.274      256225.128     1749089.553      256554.304
     1749106.533      256578.422
#Sta/Elev= 30
       0 1293.85    19.6 1285.01    29.3 1281.29    39.1 1278.06    48.9 1274.22
    58.6 1269.54    68.4 1266.57    78.2 1265.68      88 1266.14    97.7 1266.15
   107.5 1264.68   117.3  1262.2   136.8 1256.36   146.6 1255.41   151.3  1255.9
   156.4 1256.44   166.3 1258.66   205.3 1267.54   224.8 1276.17   234.6 1283.85
   244.4 1289.18   263.9 1301.45   283.4 1312.21     303  1320.1   381.2 1365.23
     391 1369.44   400.7 1373.06   410.5 1380.03   420.3  1381.5     440 1380.34
#Mann= 3 , 0 , 0
       0      .1       0   151.3    .045       0   166.3      .1       0
Bank Sta=151.3,166.3
XS Rating Curve= 0 ,0
Exp/Cntr=0.3,0.1

Type RM Length L Ch R = 1 ,31161.9 ,162.6,171.4,180.1
XS GIS Cut Line= 3
     1748691.647      256387.931     1749053.688      256648.323
     1749073.608       256663.48
#Sta/Elev= 30
       0 1306.89     9.7 1299.48    19.4 1293.58    38.8 1285.97    77.6 1272.48
      97  1267.4   106.6 1264.15   116.3 1263.47     126 1263.81   135.7 1261.94
   155.1 1254.62   164.8 1252.46   178.9 1252.04   193.9 1252.02   203.6    1252
   213.3 1252.71     223 1255.38   232.7 1260.03   242.4 1263.45   252.1 1265.43
   281.2 1269.44   290.8 1274.34   300.5 1281.64   319.9 1299.81   378.1 1311.83
   387.8 1316.86   397.5  1320.8   407.2 1323.19   436.3 1326.84     471 1329.53
#Mann= 3 , 0 , 0
       0      .1       0   178.9    .045       0   193.9      .1       0
Bank Sta=178.9,193.9
XS Rating Curve= 0 ,0
Exp/Cntr=0.3,0.1

Type RM Length L Ch R = 1 ,30990.6 ,152.1,153.5,154.9
XS GIS Cut Line= 4
     1748613.186      256439.951     1748725.463      256621.663
     1748930.358      256664.665     1749065.264      256816.917
#Sta/Elev= 30
       0 1321.26    29.1  1304.5    58.2 1290.37    87.4 1277.17    97.1 1275.49
   106.8  1271.8   126.2 1262.81   135.9 1259.01     162 1252.67   174.8 1251.37
     177 1251.46   194.2  1252.6   203.9    1255   213.6  1256.4   270.7  1257.8
   299.2 1257.86   327.8 1254.58   346.8 1253.19   375.4 1253.57   394.4 1256.88
   403.9  1259.5   413.4 1265.19     423 1269.48   461.7 1276.59   471.4 1279.17
   481.1 1280.35   539.2 1284.17   558.6 1283.33     578 1287.55   626.4 1280.68
#Mann= 3 , 0 , 0
       0      .1       0     162    .045       0     177      .1       0
#XS Ineff= 2 , 0
                          288.93         1257.82
Permanent Ineff=
       F       F
Bank Sta=162,177
XS Rating Curve= 0 ,0
Exp/Cntr=0.3,0.1

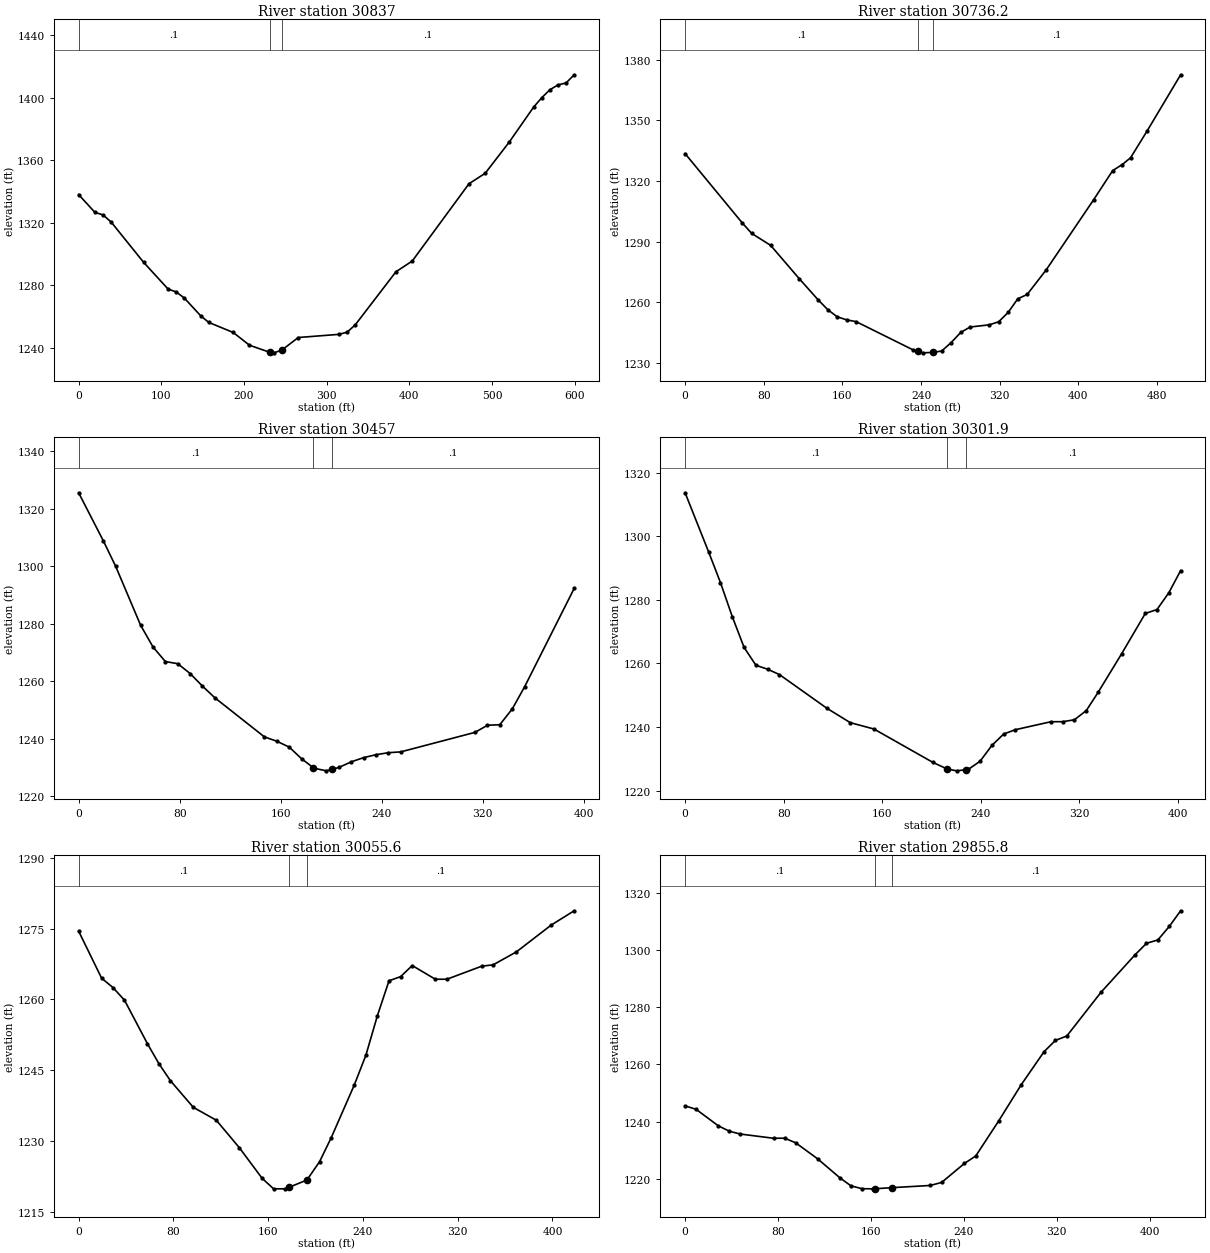
Type RM Length L Ch R = 1 ,30837   ,100.7,100.7,100.7
XS GIS Cut Line= 3
     1748489.036      256486.244     1748691.831        256868.7
     1748765.727      257017.625
#Sta/Elev= 30
       0 1337.93    19.7 1326.54    29.5 1324.94    39.4 1320.33    78.7 1294.53
   108.2 1277.51   118.1 1275.66   127.9 1271.72   147.6  1260.4   157.4 1256.18
   186.9 1249.75   206.6  1241.6   230.8 1237.12   236.1 1236.73   245.8 1238.52
   265.6 1246.53   314.8 1248.55   324.7 1249.95   334.5 1254.64   383.7 1288.58
   403.4 1295.43     472 1344.85   491.6 1351.54   520.9 1371.67   550.2  1393.9
     560 1399.87   569.8 1404.95   579.6 1408.04   589.4 1409.31   599.2 1414.54
#Mann= 3 , 0 , 0
       0      .1       0   230.8    .045       0   245.8      .1       0
Bank Sta=230.8,245.8
XS Rating Curve= 0 ,0
Exp/Cntr=0.3,0.1

Type RM Length L Ch R = 1 ,30736.2 ,273.2,279,284.8
XS GIS Cut Line= 3
     1748394.532      256521.482     1748602.851      256914.356
     1748629.279      256967.617
#Sta/Elev= 30
       0 1333.58      58 1299.32    67.7 1294.04      87 1288.12     116 1271.66
   135.3 1261.13     145 1256.29   154.7 1252.72   164.3 1251.19     174  1250.3
     232 1236.29   236.9 1235.56   241.7 1234.84   251.9 1235.05     261 1235.74
   270.7 1239.94   280.4 1244.96     290 1247.64   309.4 1248.72     319 1250.24
   328.7 1254.91   338.4  1261.6     348 1263.79   367.4 1276.01   415.7  1310.8
     435 1325.19   444.7 1328.16   453.2 1331.55   470.2 1344.98   504.1 1372.66
#Mann= 3 , 0 , 0
       0      .1       0   236.9    .045       0   251.9      .1       0
Bank Sta=236.9,251.9
XS Rating Curve= 0 ,0
Exp/Cntr=0.3,0.1

Type RM Length L Ch R = 1 ,30457   ,150.4,155,159.9
XS GIS Cut Line= 2
     1748191.976      256574.277     1748282.253      256956.279
#Sta/Elev= 30
       0 1325.64    19.6  1308.9    29.4    1300    49.1 1279.55    58.9    1272
    68.7 1266.93    78.5 1266.18    88.3 1262.77    98.1 1258.38   107.9 1254.32
   147.2  1240.7     157 1239.21   166.8 1237.16   176.6 1233.12   185.7 1230.06
   186.4 1229.82   196.3 1228.91   200.7 1229.44   206.1 1230.08   215.9 1232.04
   225.7  1233.5   235.5 1234.52   245.3 1235.22   255.1  1235.5     314  1242.3
   323.8 1244.77   333.6 1244.96   343.5 1250.47   353.3  1258.2   392.5 1292.37
#Mann= 3 , 0 , 0
       0      .1       0   185.7    .045       0   200.7      .1       0
Bank Sta=185.7,200.7
XS Rating Curve= 0 ,0
Exp/Cntr=0.3,0.1

Type RM Length L Ch R = 1 ,30301.9 ,245.8,246.2,246.7
XS GIS Cut Line= 3
     1748081.221      256582.542     1748087.895      256812.383
     1748088.254      256984.732
#Sta/Elev= 30
       0 1313.67    19.2 1294.98    28.7 1285.44    38.3 1274.74    47.9 1265.04
    57.5 1259.44    67.1 1258.18    76.6 1256.51     115 1245.95   134.1  1241.4
   153.3  1239.4   201.2  1228.9   212.7 1226.84   220.4 1226.25   227.7 1226.59
   229.9 1226.69   239.5 1229.28   249.1 1234.26   258.7 1237.84   268.2 1239.19
     297 1241.69   306.5  1241.7   316.1  1242.3   325.7  1245.2   335.3 1250.92
   354.4 1263.06   373.6 1275.73   383.1 1276.96   392.7 1282.23   402.3  1289.2
#Mann= 3 , 0 , 0
       0      .1       0   212.7    .045       0   227.7      .1       0
Bank Sta=212.7,227.7
XS Rating Curve= 0 ,0
Exp/Cntr=0.3,0.1

Type RM Length L Ch R = 1 ,30055.6 ,203.6,199.8,195.7
XS GIS Cut Line= 3
     1747849.877      256599.807     1747848.369      256793.439
     1747840.568      257017.981
#Sta/Elev= 30
       0 1274.44    19.4 1264.47      29 1262.48    38.7 1259.81    58.1 1250.57
    67.8 1246.33    77.5 1242.73    96.8 1237.09   116.2 1234.36   135.6 1228.55
   154.9 1222.04   164.6 1219.81   174.3 1219.82   177.7 1220.15   192.7 1221.68
   203.4 1225.58   213.2 1230.64   232.7 1241.83   242.5 1248.15   252.2 1256.52
     262 1263.92   271.8  1264.8   281.6 1267.15   301.1 1264.25   310.9 1264.25
   340.2 1267.01   349.9  1267.3   369.5 1270.04   398.8 1275.71   418.3 1278.76
#Mann= 3 , 0 , 0
       0      .1       0   177.7    .045       0   192.7      .1       0
Bank Sta=177.7,192.7
XS Rating Curve= 0 ,0
Exp/Cntr=0.3,0.1

Type RM Length L Ch R = 1 ,29855.8 ,160.4,160.6,160.2
XS GIS Cut Line= 3
     1747620.181      256616.948     1747648.915      256766.539
     1747693.387      257037.255
#Sta/Elev= 30
       0 1245.48     9.5 1244.27    28.6 1238.51    38.1 1236.62    47.6 1235.63
    76.2 1234.16    85.7 1234.18    95.2 1232.58   114.2 1226.95   133.3 1220.33
   142.8 1217.53   152.3 1216.53   162.1 1216.48   163.1  1216.5   178.1 1216.89
   211.1 1217.66   220.9 1218.72   240.5 1225.35   250.3 1227.98   269.9 1240.14
   289.5 1252.92   309.1 1264.43   318.9 1268.37   328.7 1269.91   358.1 1285.18
   387.5 1298.31   397.3 1302.31   407.1 1303.49   416.9  1308.2   426.7 1313.68
#Mann= 3 , 0 , 0
       0      .1       0   163.1    .045       0   178.1      .1       0
Bank Sta=163.1,178.1
XS Rating Curve= 0 ,0
Exp/Cntr=0.3,0.1

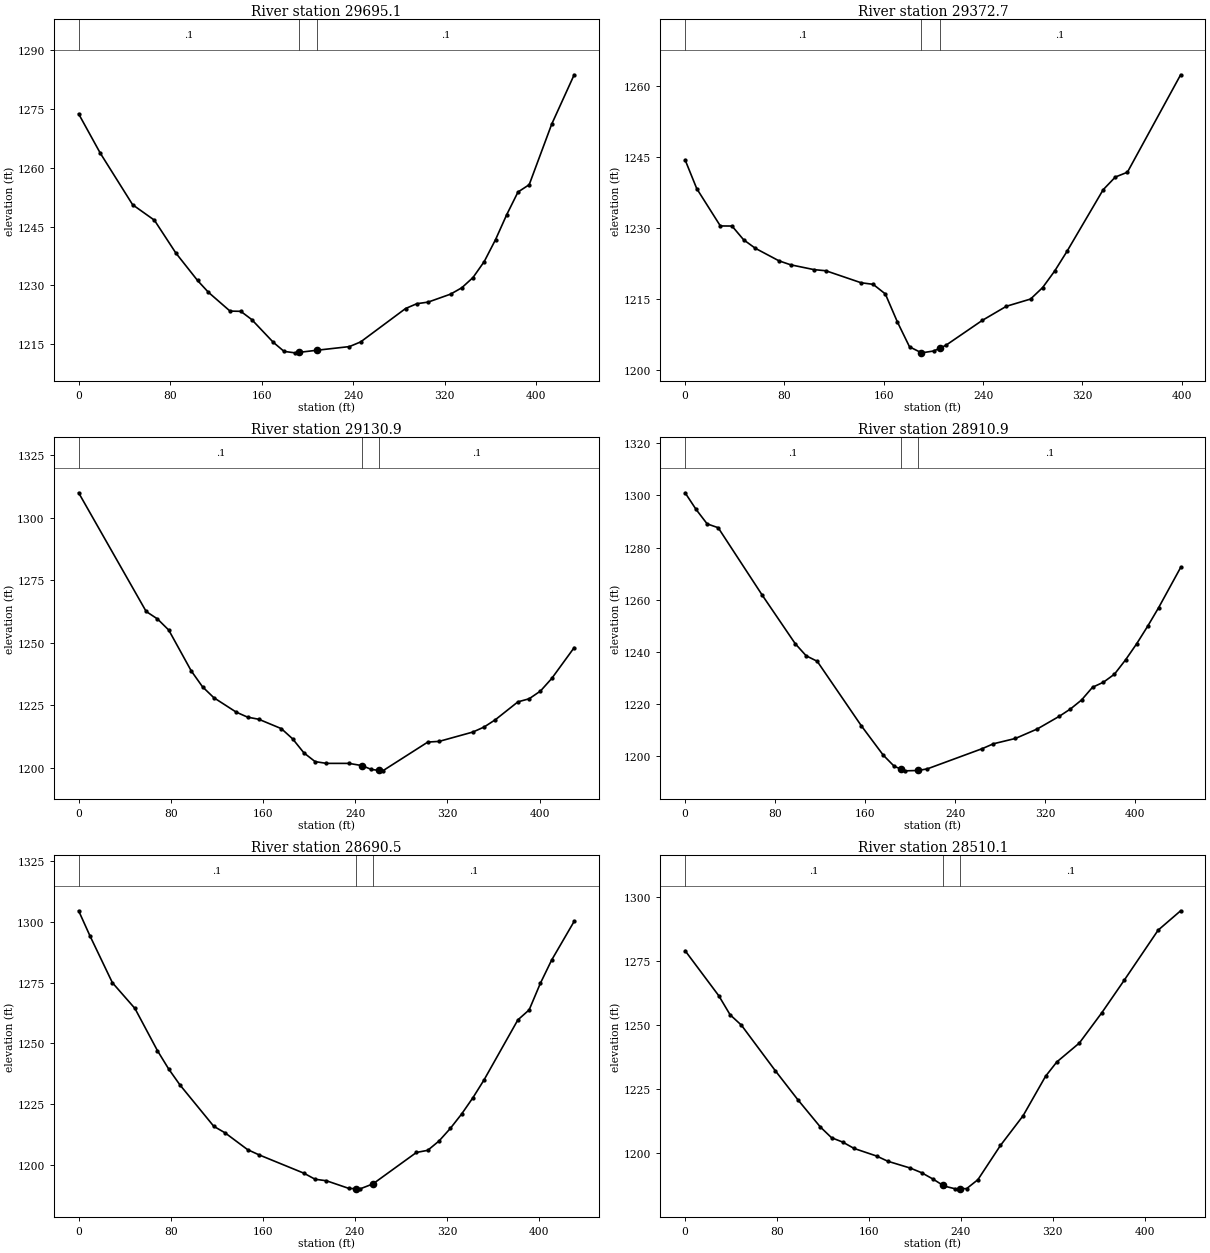
Type RM Length L Ch R = 1 ,29695.1 ,318.4,322.3,326.5
XS GIS Cut Line= 3
     1747464.093      256631.096     1747506.873      256853.812
     1747540.301      257057.302
#Sta/Elev= 30
       0  1273.7    18.9  1263.7    47.2 1250.55    66.2 1246.62      85 1238.24
   103.9 1231.27   113.4 1228.26   132.3 1223.47   141.7 1223.41   151.2 1221.33
   170.1 1215.52   179.5 1213.21     189 1212.84   192.9 1212.97   207.9 1213.49
   236.6 1214.43   246.4 1215.62   285.7 1224.13   295.5 1225.35   305.4 1225.76
     325 1227.79   334.8 1229.41   344.6 1232.02   354.4 1236.08   364.3 1241.68
   374.1 1248.05   383.9 1253.79   393.7 1255.66   413.4  1271.1     433 1283.65
#Mann= 3 , 0 , 0
       0      .1       0   192.9    .045       0   207.9      .1       0
Bank Sta=192.9,207.9
XS Rating Curve= 0 ,0
Exp/Cntr=0.3,0.1

Type RM Length L Ch R = 1 ,29372.7 ,237.1,241.7,246.4
XS GIS Cut Line= 4
      1747212.51      256722.859     1747216.624      256864.552
     1747217.152      257118.125      1747217.16       257121.99
#Sta/Elev= 30
       0 1244.39     9.4  1238.3    28.4 1230.42    37.8  1230.4    47.2 1227.48
    56.7 1225.68    75.6 1223.05      85 1222.21     104 1221.18   113.4 1220.95
   141.8 1218.41   151.5 1218.08   161.3 1216.05     171 1210.14   180.8 1204.87
   190.1 1203.65   190.5  1203.6   200.3 1203.99   205.1 1204.58     210 1205.18
   239.3 1210.44   258.8 1213.44   278.3 1214.97     288 1217.39   297.8 1220.92
   307.6 1225.03   336.8 1238.08   346.6 1240.76   356.3 1241.77   399.2 1262.37
#Mann= 3 , 0 , 0
       0      .1       0   190.1    .045       0   205.1      .1       0
Bank Sta=190.1,205.1
XS Rating Curve= 0 ,0
Exp/Cntr=0.3,0.1

Type RM Length L Ch R = 1 ,29130.9 ,214.7,219.9,225
XS GIS Cut Line= 2
     1747028.048      256670.156     1746941.185      257091.326
#Sta/Elev= 30
       0 1309.95    58.6 1262.47    68.4 1259.49    78.2 1255.03    97.7 1238.71
   107.5 1232.34   117.3 1227.98   136.8 1222.19   146.6  1220.2   156.4 1219.34
   175.9  1215.6   185.7 1211.52   195.5  1205.9   205.2 1202.41     215 1201.71
   234.6  1201.7   245.9 1200.81   254.1 1199.26   260.9 1198.89   263.9 1198.72
     303 1210.23   312.8  1210.5   342.1 1214.24   351.8 1216.24   361.6 1219.16
   381.2 1226.32   390.9 1227.54   400.7 1230.62   410.5 1235.66     430 1248.01
#Mann= 3 , 0 , 0
       0      .1       0   245.9    .045       0   260.9      .1       0
Bank Sta=245.9,260.9
XS Rating Curve= 0 ,0
Exp/Cntr=0.3,0.1

Type RM Length L Ch R = 1 ,28910.9 ,220.1,220.3,220.6
XS GIS Cut Line= 2
      1746875.62      256626.605     1746690.433      257026.124
#Sta/Elev= 30
       0 1300.99     9.8 1294.59    19.6 1289.08    29.4 1287.61    68.5 1261.81
    97.9 1243.18   107.6 1238.55   117.4 1236.46   156.6 1211.76   176.1  1200.5
   185.9 1196.22   192.2 1195.11   195.7 1194.49   207.2 1194.63   215.3 1195.25
   264.2 1203.01     274 1204.85   293.6  1206.9   313.1 1210.55   332.7 1215.42
   342.5 1218.19   352.3 1221.61   362.1  1226.5   371.8 1228.44   381.6 1231.52
   391.4 1236.97   401.2 1243.08     411 1249.81   420.8 1256.96   440.4 1272.38
#Mann= 3 , 0 , 0
       0      .1       0   192.2    .045       0   207.2      .1       0
Bank Sta=192.2,207.2
XS Rating Curve= 0 ,0
Exp/Cntr=0.3,0.1

Type RM Length L Ch R = 1 ,28690.5 ,174.6,180.5,186.3
XS GIS Cut Line= 2
     1746688.225      256523.856     1746507.227      256914.337
#Sta/Elev= 30
       0 1304.43     9.8 1294.18    29.3 1274.93    48.9 1264.36    68.5    1247
    78.2 1239.53      88 1232.98   117.4    1216   127.2 1213.32   146.7 1206.45
   156.5 1204.33   195.6 1196.78   205.4 1194.28   215.2 1193.67   234.8 1190.51
   240.6 1190.41   244.5 1190.35   255.6 1192.37   293.4 1205.28   303.2 1206.15
     313 1209.97   322.8 1215.12   332.6 1221.02   342.4 1227.69   352.1 1235.03
   381.5 1259.67   391.3 1263.77     401 1274.64   410.8 1284.18   430.4  1300.1
#Mann= 3 , 0 , 0
       0      .1       0   240.6    .045       0   255.6      .1       0
Bank Sta=240.6,255.6
XS Rating Curve= 0 ,0
Exp/Cntr=0.3,0.1

Type RM Length L Ch R = 1 ,28510.1 ,136.5,136.3,136
XS GIS Cut Line= 2
     1746605.321      256447.209     1746334.609      256783.125
#Sta/Elev= 30
       0 1278.98    29.4 1261.35    39.2 1253.96      49 1249.93    78.4 1232.23
      98 1220.92   117.7 1210.22   127.5 1206.01   137.3 1204.29   147.1 1201.83
   166.7 1198.87   176.5 1196.83   196.1 1194.16   205.9 1192.36   215.7 1189.91
   224.5 1187.43   225.5 1187.15   235.3 1186.07   239.5 1186.11   245.1 1186.16
   254.9 1189.64   274.5 1202.98   294.2 1214.55   313.8 1229.98   323.6 1235.57
   343.2 1242.94   362.8 1254.78   382.4 1267.52   411.8 1286.98   431.4 1294.54
#Mann= 3 , 0 , 0
       0      .1       0   224.5    .045       0   239.5      .1       0
Bank Sta=224.5,239.5
XS Rating Curve= 0 ,0
Exp/Cntr=0.3,0.1