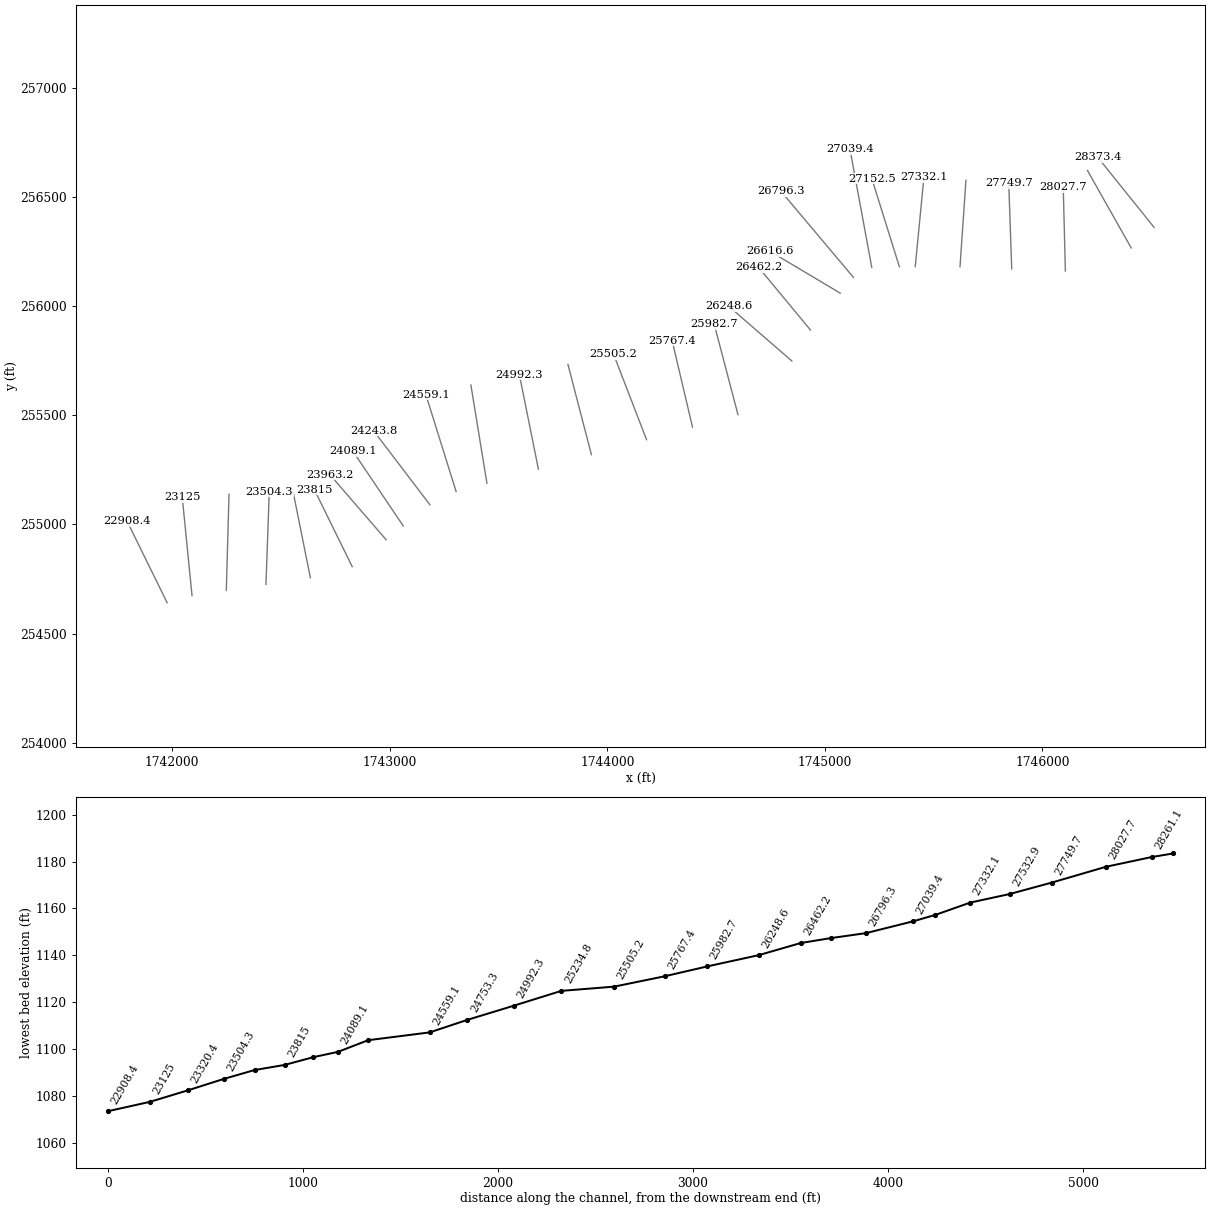
HEC-RAS study ELKCRK.prj: ELKCRK

--- ELKCRK.g01 (geometry) --- (continued)

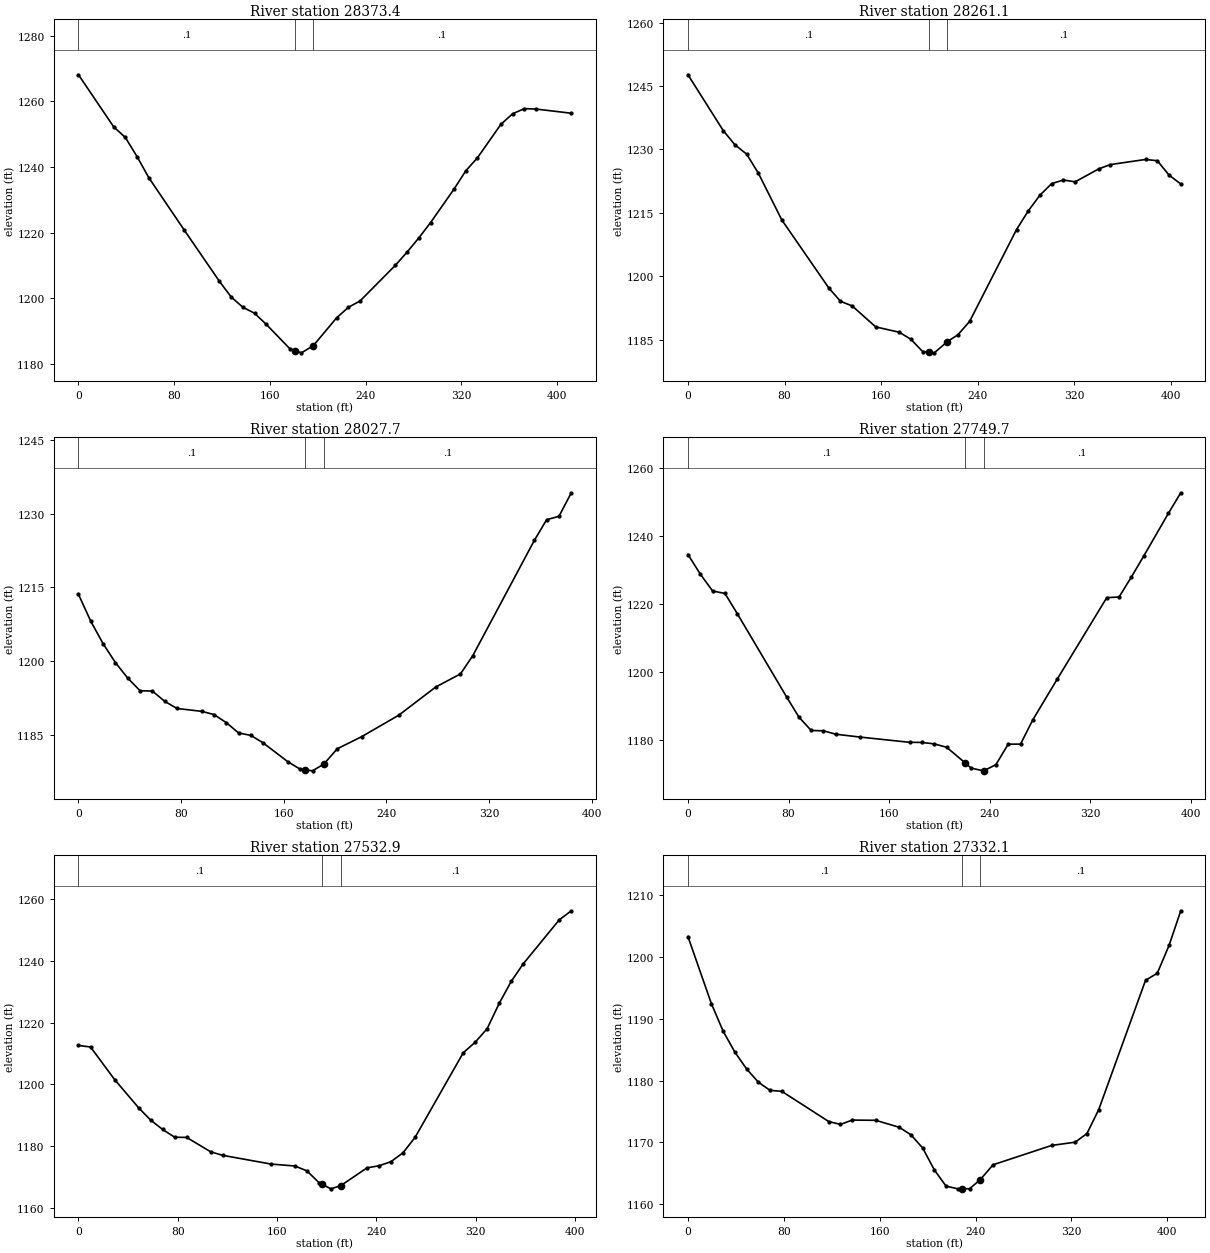
Type RM Length L Ch R = 1 ,28373.4 ,115.8,112.2,108.6
XS GIS Cut Line= 2
     1746513.034      256361.887      1746254.61      256682.555
#Sta/Elev= 30
       0 1268.06    29.4 1252.22    39.2 1248.98      49 1243.11    58.8 1236.72
    88.2  1220.9   117.7 1205.25   127.5 1200.49   137.3 1197.34   147.1 1195.51
   156.9 1192.13   176.5 1184.75   181.2 1184.13   186.3 1183.46   196.2 1185.63
   215.7 1194.12   225.5  1197.3   235.3 1199.25   264.8  1210.1   274.6 1214.12
   284.4 1218.43   294.2 1223.09   313.8 1233.28   323.6 1238.82   333.4 1242.82
     353 1252.99   362.8 1256.21   372.6 1257.76   382.4 1257.63   411.8 1256.36
#Mann= 3 , 0 , 0
       0      .1       0   181.2    .045       0   196.2      .1       0
Bank Sta=181.2,196.2
XS Rating Curve= 0 ,0
Exp/Cntr=0.3,0.1

Type RM Length L Ch R = 1 ,28261.1 ,245.5,233.4,221.2
XS GIS Cut Line= 2
     1746408.007      256267.478     1746206.902      256622.579
#Sta/Elev= 30
       0 1247.67    29.2 1234.48    38.9  1231.1    48.6  1228.9    58.3 1224.39
    77.7 1213.34   116.6 1197.25   126.3  1194.1     136 1192.99   155.5 1188.03
   174.9 1186.78   184.6 1185.11   194.3 1182.21   199.8 1182.03     204  1181.9
   214.8 1184.55   223.5 1186.16   233.2 1189.32   272.1 1211.06   281.8 1215.47
   291.5  1219.2   301.2 1221.93   310.9 1222.78   320.6 1222.35   340.1  1225.4
   349.8 1226.43   378.9 1227.64   388.7 1227.34   398.4 1223.94   408.1 1221.84
#Mann= 3 , 0 , 0
       0      .1       0   199.8    .045       0   214.8      .1       0
Bank Sta=199.8,214.8
XS Rating Curve= 0 ,0
Exp/Cntr=0.3,0.1

Type RM Length L Ch R = 1 ,28027.7 ,276.3,278,279.6
XS GIS Cut Line= 2
     1746105.366      256161.551     1746095.502      256545.517
#Sta/Elev= 30
       0 1213.59     9.6 1208.12    19.2 1203.57    28.8 1199.74    38.4 1196.59
      48 1194.03    57.6 1193.97    67.2 1191.88    76.8 1190.43      96 1189.85
   105.6  1189.2   115.2 1187.56   124.8 1185.46   134.4 1184.96     144 1183.43
   163.2 1179.61   172.8  1178.1   176.3 1177.98   182.4 1177.77   191.3 1179.16
   201.6 1182.23   220.8 1184.72   249.7 1189.08   278.5  1194.8   297.7 1197.44
   307.3 1201.14   355.3 1224.56   364.9 1228.76   374.5 1229.44   384.1 1234.22
#Mann= 3 , 0 , 0
       0      .1       0   176.3    .045       0   191.3      .1       0
Bank Sta=176.3,191.3
XS Rating Curve= 0 ,0
Exp/Cntr=0.3,0.1

Type RM Length L Ch R = 1 ,27749.7 ,219.1,216.7,214.4
XS GIS Cut Line= 2
     1745858.657      256171.724     1745845.066      256563.548
#Sta/Elev= 29
       0 1234.59     9.8 1228.85    19.6 1223.87    29.4 1223.16    39.2 1217.24
    78.4 1192.79    88.2 1186.87      98 1182.89   107.8 1182.79   117.6 1181.79
   137.2 1180.94   176.4 1179.41   186.2 1179.38     196 1178.94   205.8 1177.96
   220.2 1173.47   225.4 1171.81   235.2 1171.03     245 1172.84   254.8 1178.87
   264.6 1178.88   274.4 1186.04     294  1198.1   333.2 1221.91     343 1222.11
   352.8 1227.98   362.7 1234.19   382.3 1246.72   392.1 1252.73
#Mann= 3 , 0 , 0
       0      .1       0   220.2    .045       0   235.2      .1       0
Bank Sta=220.2,235.2
XS Rating Curve= 0 ,0
Exp/Cntr=0.3,0.1

Type RM Length L Ch R = 1 ,27532.9 ,201.4,200.9,200.3
XS GIS Cut Line= 2
     1745620.963      256181.526     1745648.309      256577.715
#Sta/Elev= 30
       0 1212.61     9.7 1212.11    29.1 1201.56    48.4 1192.43    58.1 1188.44
    67.8 1185.38    77.5 1182.87    87.2  1182.8   106.6 1178.12   116.2    1177
     155 1174.18   174.4 1173.54     184 1171.98   193.7 1168.18   196.3 1167.63
   203.4 1166.14   211.3 1167.17   232.5 1172.94   242.2 1173.62   251.8 1174.95
   261.5 1177.83   271.2 1182.81     310 1210.22   319.6 1213.63   329.3 1218.05
     339 1226.26   348.7 1233.37   358.4 1239.09   387.4 1253.32   397.1 1256.26
#Mann= 3 , 0 , 0
       0      .1       0   196.3    .045       0   211.3      .1       0
Bank Sta=196.3,211.3
XS Rating Curve= 0 ,0
Exp/Cntr=0.3,0.1

Type RM Length L Ch R = 1 ,27332.1 ,170.5,179.6,188.7
XS GIS Cut Line= 2
     1745415.159      256182.263     1745455.135      256591.623
#Sta/Elev= 30
       0 1203.23    19.6 1192.38    29.4 1187.95    39.2 1184.57      49 1181.86
    58.8 1179.72    68.6 1178.41    78.3 1178.26   117.5 1173.38   127.3 1172.92
   137.1 1173.62   156.7 1173.58   176.3 1172.46   186.1 1171.24   195.9 1169.11
   205.6 1165.58   215.4 1162.96   225.2 1162.52   228.9 1162.53     235 1162.54
   243.9 1163.99   254.6  1166.4   303.6 1169.53   323.2 1170.05     333 1171.45
   342.8  1175.3   381.9 1196.18   391.7 1197.32   401.5  1201.8   411.3  1207.4
#Mann= 3 , 0 , 0
       0      .1       0   228.9    .045       0   243.9      .1       0
Bank Sta=228.9,243.9
XS Rating Curve= 0 ,0
Exp/Cntr=0.3,0.1

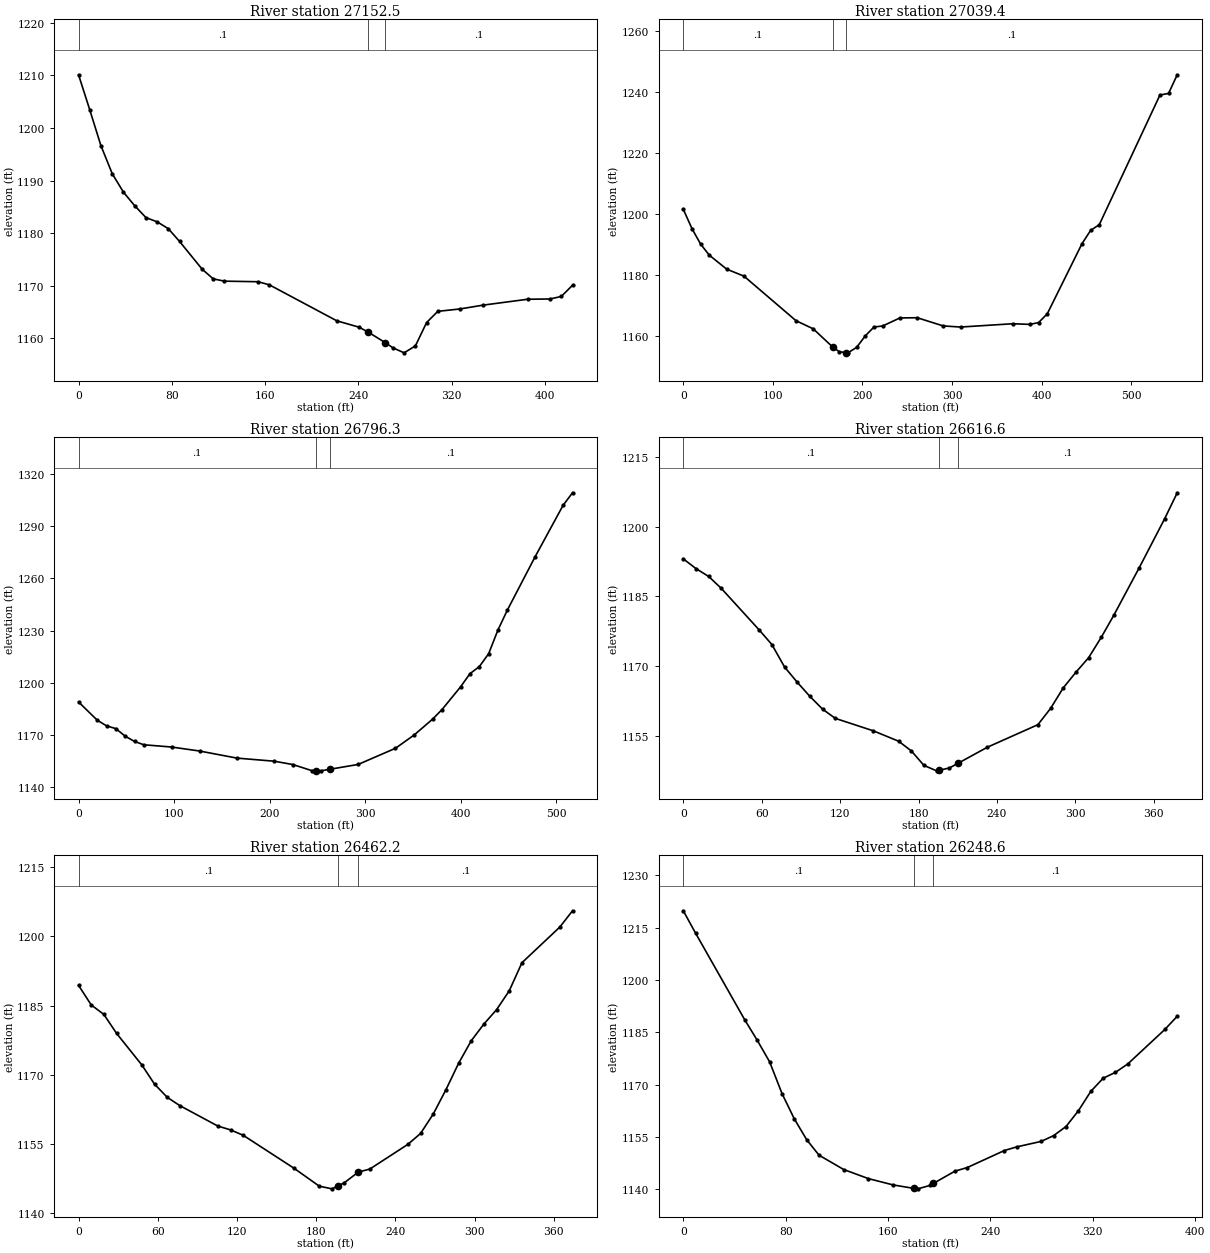
Type RM Length L Ch R = 1 ,27152.5 ,116.4,113,108.3
XS GIS Cut Line= 2
     1745342.385      256180.986     1745215.765      256585.108
#Sta/Elev= 30
       0 1210.13     9.6 1203.47    19.2 1196.64    28.9 1191.31    38.5 1187.81
    48.1 1185.24    57.8 1182.97    67.4 1182.17      77 1180.86    86.6 1178.44
   105.9 1173.18   115.5 1171.32   125.1 1170.89     154 1170.78   163.6 1170.19
   221.4 1163.35   240.6 1162.13   247.8 1161.27   262.8 1159.22   269.5 1158.22
   279.1 1157.26   288.8 1158.58   298.4 1163.02     308 1165.15   327.2 1165.61
   346.5 1166.32     385 1167.45   404.2  1167.5   413.9 1167.98   423.5 1170.11
#Mann= 3 , 0 , 0
       0      .1       0   247.8    .045       0   262.8      .1       0
Bank Sta=247.8,262.8
XS Rating Curve= 0 ,0
Exp/Cntr=0.3,0.1

Type RM Length L Ch R = 1 ,27039.4 ,231.1,242.7,255.7
XS GIS Cut Line= 2
     1745215.284      256178.756     1745114.887       256721.05
#Sta/Elev= 30
       0 1201.57     9.7 1195.22    19.4 1190.14      29 1186.55    48.4 1181.96
    67.7 1179.67   125.8 1165.08   145.1  1162.4   166.9 1156.42   174.2 1154.91
   181.9 1154.61   183.8 1154.54   193.5 1156.32   203.2 1160.09   212.9    1163
   222.5 1163.33   241.9 1165.97   261.2 1166.04   290.3 1163.35   309.6 1162.99
   367.7 1164.07     387 1163.86   396.7 1164.45   406.4 1167.33   445.1 1190.26
   454.8 1194.66   464.4 1196.49   532.2 1238.99   541.8 1239.51   551.5 1245.62
#Mann= 3 , 0 , 0
       0      .1       0   166.9    .045       0   181.9      .1       0
Bank Sta=166.9,181.9
XS Rating Curve= 0 ,0
Exp/Cntr=0.3,0.1

Type RM Length L Ch R = 1 ,26796.3 ,172.2,179.7,187.2
XS GIS Cut Line= 2
     1745131.205      256132.562     1744797.632      256527.783
#Sta/Elev= 30
       0 1189.01    19.5 1178.59    29.3 1175.29      39 1173.72    48.8 1169.39
    58.6 1166.36    68.3 1164.45    97.6 1163.14   126.8 1160.85   165.9 1156.79
   204.9 1155.02   224.4  1153.1     244 1149.65   248.1 1149.58   253.7 1149.49
   263.1 1150.39   292.7 1153.15   331.8 1162.42   351.3 1170.02   370.8 1179.19
   380.6 1184.67   400.1 1197.74   409.8 1205.24   419.6 1209.26   429.4  1216.7
   439.1 1230.26   448.9 1241.63   478.1 1272.39   507.4 1301.89   517.2 1309.02
#Mann= 3 , 0 , 0
       0      .1       0   248.1    .045       0   263.1      .1       0
Bank Sta=248.1,263.1
XS Rating Curve= 0 ,0
Exp/Cntr=0.3,0.1

Type RM Length L Ch R = 1 ,26616.6 ,162.1,154.4,146.6
XS GIS Cut Line= 2
     1745070.199      256060.464     1744745.354      256253.556
#Sta/Elev= 30
       0 1193.11     9.7 1191.02    19.4 1189.32    29.1 1186.74    58.1 1177.77
    67.8 1174.62    77.5 1169.77    87.2 1166.49    96.9 1163.43   106.6 1160.68
   116.3  1158.7   145.4 1156.01   164.7 1153.78   174.4  1151.7   184.1 1148.56
   193.8 1147.38   195.4 1147.48   203.5 1147.99   210.4 1149.04   232.6 1152.47
   271.3 1157.34     281 1160.85   290.7 1165.28   300.4 1168.66   310.1 1171.79
   319.8  1176.2   329.4 1180.96   348.8 1191.19   368.2 1201.73   377.9 1207.37
#Mann= 3 , 0 , 0
       0      .1       0   195.4    .045       0   210.4      .1       0
Bank Sta=195.4,210.4
XS Rating Curve= 0 ,0
Exp/Cntr=0.3,0.1

Type RM Length L Ch R = 1 ,26462.2 ,214.6,214.8,215
XS GIS Cut Line= 2
     1744933.809      255891.045      1744694.87      256178.924
#Sta/Elev= 30
       0 1189.39     9.6 1185.15    19.2 1183.08    28.8 1178.98      48 1172.11
    57.6 1167.95    67.2 1165.12    76.7 1163.32   105.5 1158.89   115.1 1158.06
   124.7 1156.89   163.1 1149.76   182.3 1145.86   191.9 1145.28   196.8 1145.97
   201.4 1146.62   211.8  1148.9   220.6 1149.57   249.4 1154.92     259 1157.28
   268.6 1161.48   278.2 1166.74   287.8 1172.48   297.4 1177.38     307 1181.01
   316.6 1184.13   326.2 1188.22   335.8  1194.3   364.5 1202.03   374.1 1205.56
#Mann= 3 , 0 , 0
       0      .1       0   196.8    .045       0   211.8      .1       0
Bank Sta=196.8,211.8
XS Rating Curve= 0 ,0
Exp/Cntr=0.3,0.1

Type RM Length L Ch R = 1 ,26248.6 ,274.3,264.2,253.9
XS GIS Cut Line= 2
     1744848.202      255749.183     1744556.248      256001.617
#Sta/Elev= 30
       0 1219.83     9.6 1213.42    48.2 1188.46    57.9 1182.65    67.5  1176.5
    77.2  1167.4    86.8 1160.14    96.5 1154.17   106.1 1149.76   125.4 1145.65
   144.7 1143.05     164 1141.24   180.5 1140.23   183.3 1140.12     193 1141.12
   195.5 1141.69   212.3 1145.19   221.9 1146.22   250.9  1151.1   260.5 1152.14
   279.8 1153.73   289.5  1155.4   299.1 1157.99   308.8 1162.52   318.4 1168.03
   328.1 1171.83   337.7 1173.51   347.4 1175.94   376.3  1185.8     386 1189.59
#Mann= 3 , 0 , 0
       0      .1       0   180.5    .045       0   195.5      .1       0
Bank Sta=180.5,195.5
XS Rating Curve= 0 ,0
Exp/Cntr=0.3,0.1

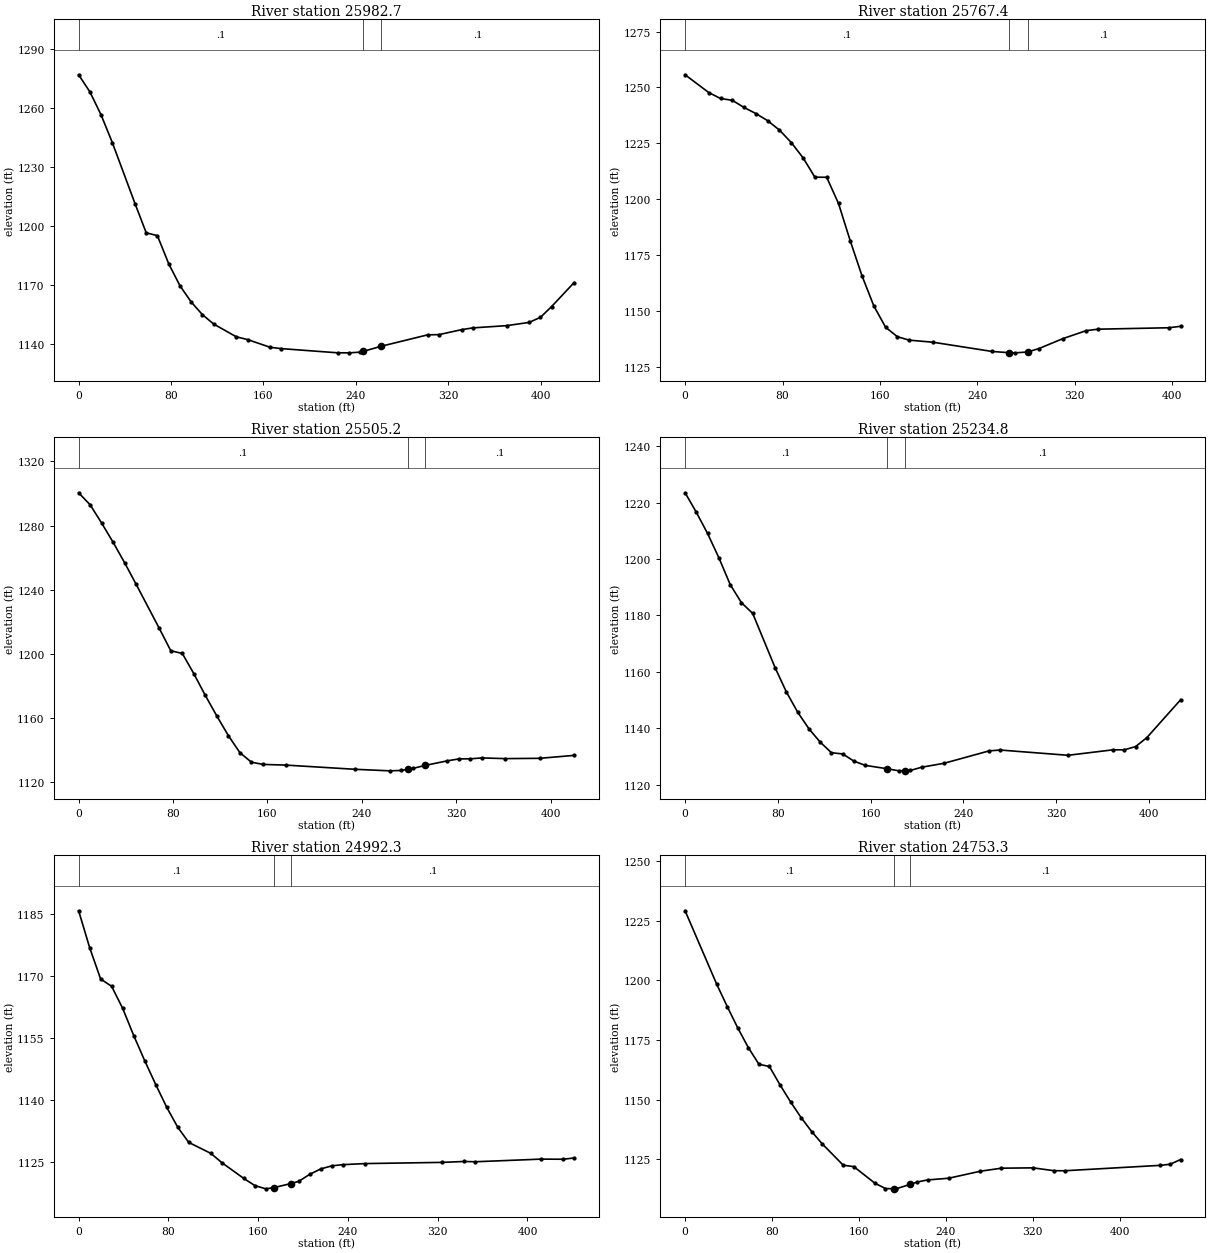
Type RM Length L Ch R = 1 ,25982.7 ,216.3,215.3,214.5
XS GIS Cut Line= 2
     1744600.379      255503.316     1744490.982      255918.136
#Sta/Elev= 30
       0 1276.65     9.8 1267.92    19.5 1256.18    29.2 1242.13    48.8  1211.2
    58.5 1196.34    68.2 1194.87      78 1180.57    87.8 1169.35    97.5 1161.13
   107.2 1154.71     117 1149.92   136.5 1143.48   146.2 1142.08   165.8 1138.14
   175.5 1137.46   224.2 1135.34     234 1135.32   243.8 1135.66   246.4 1136.04
   261.4 1138.59   302.2 1144.47     312 1144.58   331.5  1147.1   341.2    1148
   370.5 1149.14     390 1150.78   399.8 1153.37   409.5 1158.87     429 1171.07
#Mann= 3 , 0 , 0
       0      .1       0   246.4    .045       0   261.4      .1       0
Bank Sta=246.4,261.4
XS Rating Curve= 0 ,0
Exp/Cntr=0.3,0.1

Type RM Length L Ch R = 1 ,25767.4 ,258.9,262.2,265.4
XS GIS Cut Line= 2
     1744391.276      255446.373     1744297.688       255842.43
#Sta/Elev= 30
       0 1255.66    19.4 1247.72    29.1 1245.04    38.8 1244.22    48.4 1241.02
    58.1 1238.31    67.8 1235.11    77.5  1230.9    87.2 1225.32    96.9 1218.48
   106.6 1209.81   116.3 1209.77     126 1198.04   135.6 1181.38   145.3 1165.65
     155 1152.19   164.7  1142.6   174.4 1138.38   184.1 1136.85   203.5 1135.93
   251.9 1131.81   266.4 1131.21   271.3 1131.17   281.4 1131.56   290.7  1133.1
   310.1  1137.5   329.4  1141.1   339.1 1141.76   397.3  1142.4     407 1143.05
#Mann= 3 , 0 , 0
       0      .1       0   266.4    .045       0   281.4      .1       0
Bank Sta=266.4,281.4
XS Rating Curve= 0 ,0
Exp/Cntr=0.3,0.1

Type RM Length L Ch R = 1 ,25505.2 ,272.7,270.3,268
XS GIS Cut Line= 2
     1744180.026      255388.845     1744028.482      255780.544
#Sta/Elev= 30
       0 1300.45     9.8  1292.9    19.5 1281.53    29.3 1269.41    39.1 1256.58
    48.8 1243.17    68.4 1215.67    78.1 1201.74    87.9 1200.04    97.7 1187.31
   107.4 1173.78   117.2 1160.87     127 1148.61   136.7 1138.03   146.5 1132.09
   156.3 1130.72   175.8 1130.28   234.4 1127.66   263.7  1126.7   273.5 1126.95
   278.8 1127.64   283.2 1128.21   293.8  1130.1   312.6 1132.97   322.3 1134.15
   332.1 1134.22   341.8 1134.78   361.4 1134.34   390.7 1134.52     420 1136.36
#Mann= 3 , 0 , 0
       0      .1       0   278.8    .045       0   293.8      .1       0
Bank Sta=278.8,293.8
XS Rating Curve= 0 ,0
Exp/Cntr=0.3,0.1

Type RM Length L Ch R = 1 ,25234.8 ,243.7,242.4,241.2
XS GIS Cut Line= 2
     1743926.656      255319.847     1743818.739      255733.556
#Sta/Elev= 30
       0 1223.45     9.7 1216.53    19.4 1209.03    29.2 1200.37    38.9 1190.93
    48.6  1184.5    58.3 1180.72    77.7 1161.43    87.4 1152.86    97.2 1145.65
   106.9 1139.78   116.6 1135.06   126.3 1131.32     136 1130.89   145.8 1128.31
   155.5 1126.84   174.5 1125.63   184.6  1124.9   189.5 1124.97   194.3 1125.03
   204.1 1126.18   223.5 1127.58   262.4 1131.98   272.1 1132.27   330.4 1130.41
   369.2 1132.35     379 1132.35   388.7 1133.49   398.4 1136.65   427.6  1150.1
#Mann= 3 , 0 , 0
       0      .1       0   174.5    .045       0   189.5      .1       0
Bank Sta=174.5,189.5
XS Rating Curve= 0 ,0
Exp/Cntr=0.3,0.1

Type RM Length L Ch R = 1 ,24992.3 ,239.8,239,238.2
XS GIS Cut Line= 2
     1743682.957      255253.482     1743595.535      255686.374
#Sta/Elev= 30
       0 1185.89     9.8 1176.99    19.6 1169.38    29.4 1167.62    39.3 1162.25
    49.1  1155.7    58.9 1149.61    68.7 1143.86    78.5 1138.35    88.3 1133.53
    98.1 1129.86   117.8  1127.2   127.6 1124.96   147.2 1121.13     157 1119.42
   166.8 1118.62   174.3 1118.93   189.3 1119.91   196.3 1120.45   206.1 1122.16
   215.9 1123.45   225.7 1124.19   235.5 1124.47   255.2 1124.73   323.9 1125.02
   343.5 1125.24   353.3 1125.17   412.2 1125.81   431.8 1125.78   441.6 1126.09
#Mann= 3 , 0 , 0
       0      .1       0   174.3    .045       0   189.3      .1       0
Bank Sta=174.3,189.3
XS Rating Curve= 0 ,0
Exp/Cntr=0.3,0.1

Type RM Length L Ch R = 1 ,24753.3 ,185.7,193.5,198.9
XS GIS Cut Line= 2
       1743446.3      255189.036     1743372.554       255639.24
#Sta/Elev= 30
       0 1229.16    29.1 1198.38    38.8 1188.99    48.5 1180.02    58.2  1171.8
      68 1164.78    77.6 1163.87    87.4 1156.14    97.1 1149.03   106.8 1142.43
   116.5  1136.6   126.2 1131.44   145.6 1122.46   155.3 1121.88   174.7 1114.93
   184.4 1112.69   192.3 1112.58   194.1 1112.56   207.3 1114.44   213.5  1115.4
   223.2 1116.29   242.7 1117.01   271.8 1119.95   291.2 1121.22   320.3 1121.36
   339.7 1120.16   349.4 1120.14   436.8 1122.39   446.5 1122.86   456.2 1124.86
#Mann= 3 , 0 , 0
       0      .1       0   192.3    .045       0   207.3      .1       0
Bank Sta=192.3,207.3
XS Rating Curve= 0 ,0
Exp/Cntr=0.3,0.1

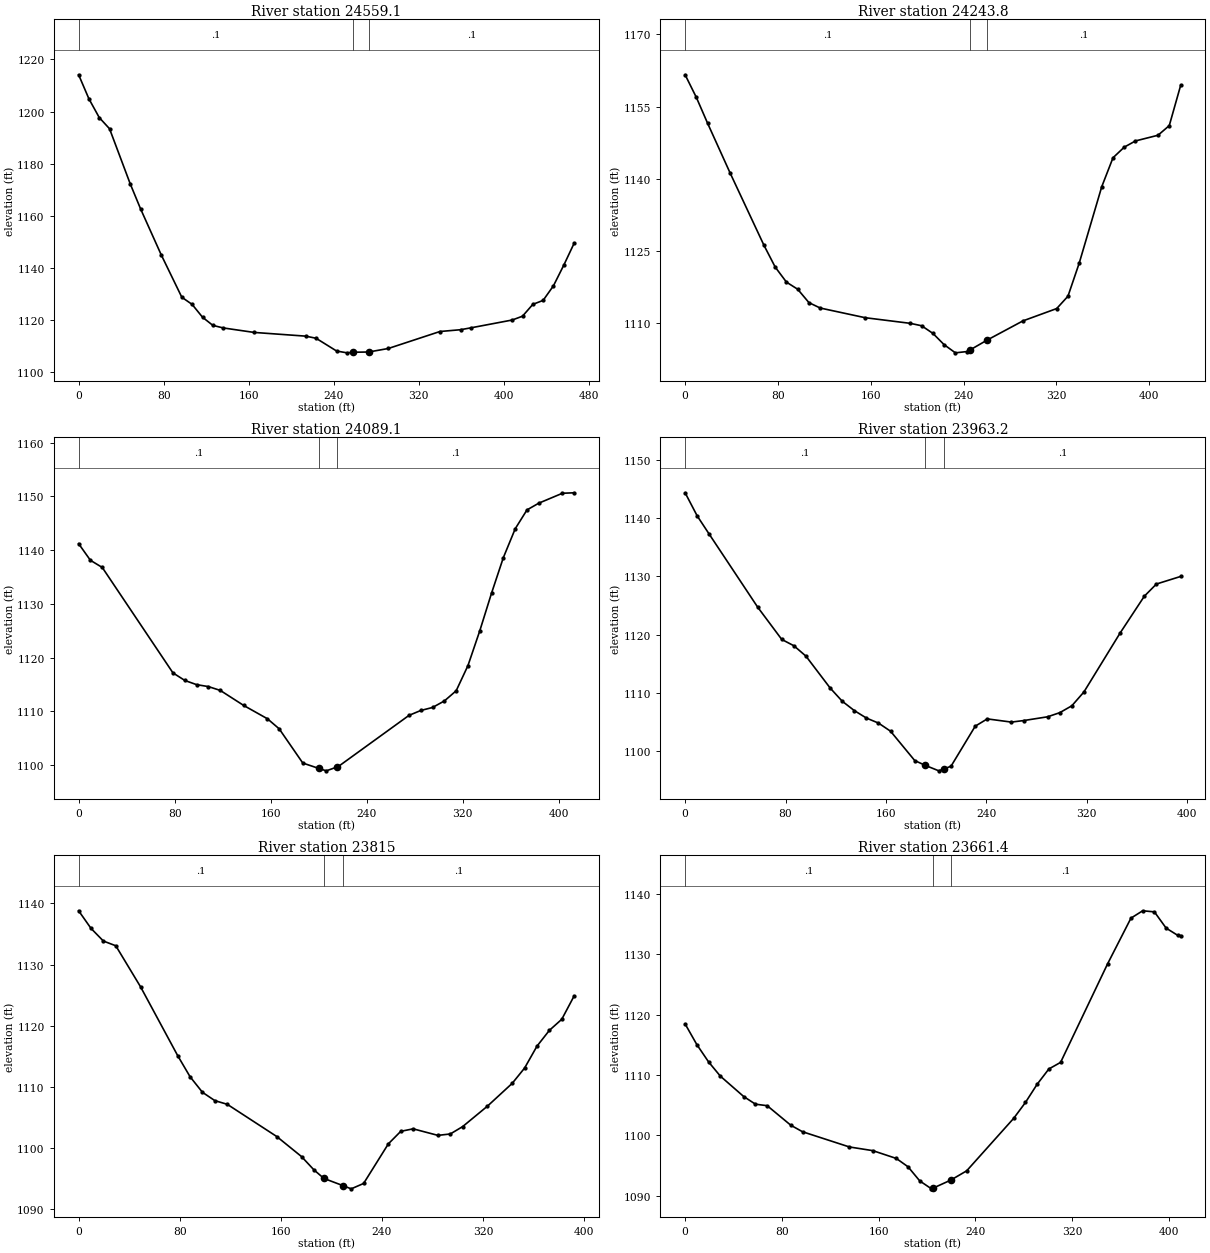
Type RM Length L Ch R = 1 ,24559.1 ,274.9,315.7,312.3
XS GIS Cut Line= 2
     1743304.849      255150.516     1743165.439       255595.46
#Sta/Elev= 30
       0 1214.12     9.7 1204.86    19.4 1197.67    29.1 1193.36    48.6 1172.14
    58.3 1162.56    77.7 1144.91    97.1 1128.59   106.8 1125.83   116.6  1120.9
   126.3 1117.77     136 1116.79   165.1 1115.06   213.7 1113.63   223.4 1112.82
   242.8  1107.9   252.6 1107.21   257.9 1107.44   272.9 1107.53   291.4 1108.88
     340 1115.41   359.4  1116.1   369.1 1116.82     408 1119.83   417.7  1121.3
   427.4 1125.84   437.1 1127.38   446.8 1132.97   456.6 1140.96   466.3 1149.36
#Mann= 3 , 0 , 0
       0      .1       0   257.9    .045       0   272.9      .1       0
Bank Sta=257.9,272.9
XS Rating Curve= 0 ,0
Exp/Cntr=0.3,0.1

Type RM Length L Ch R = 1 ,24243.8 ,156.2,154.8,153.4
XS GIS Cut Line= 2
       1743184.2       255090.45     1742925.198      255429.865
#Sta/Elev= 30
       0 1161.59     9.7 1156.88    19.4 1151.51    38.8 1141.19    67.9 1126.22
    77.6 1121.69    87.3 1118.56      97 1117.08   106.7  1114.3   116.4 1113.18
   155.2 1111.17   194.1    1110   203.8  1109.5   213.5 1107.92   223.2 1105.57
   232.9 1103.88   242.6 1104.14   245.5 1104.48   260.5 1106.56   291.1 1110.51
   320.2 1113.07   329.9 1115.63   339.6  1122.5     359 1138.35   368.7 1144.36
   378.4 1146.57   388.1 1147.86   407.5 1149.04   417.2 1151.04     427 1159.38
#Mann= 3 , 0 , 0
       0      .1       0   245.5    .045       0   260.5      .1       0
Bank Sta=245.5,260.5
XS Rating Curve= 0 ,0
Exp/Cntr=0.3,0.1

Type RM Length L Ch R = 1 ,24089.1 ,122.9,125.7,128.4
XS GIS Cut Line= 2
     1743061.698      254993.119     1742830.668      255335.335
#Sta/Elev= 30
       0 1141.21     9.8 1138.12    19.7 1136.78    78.6 1117.15    88.5 1115.74
    98.3 1114.96   108.1  1114.6     118 1113.89   137.6 1111.08   157.3 1108.61
   167.1 1106.74   186.8 1100.36     200 1099.37   206.4 1098.91     215  1099.6
   216.3  1099.7   275.3 1109.24   285.1 1110.15   294.9 1110.71   304.8 1111.93
   314.6 1113.82   324.4  1118.5   334.2 1124.94   344.1 1132.02   353.9 1138.61
   363.8 1143.99   373.6  1147.5   383.4 1148.75   403.1  1150.6   412.9 1150.69
#Mann= 3 , 0 , 0
       0      .1       0     200    .045       0     215      .1       0
Bank Sta=200,215
XS Rating Curve= 0 ,0
Exp/Cntr=0.3,0.1

Type RM Length L Ch R = 1 ,23963.2 ,155.1,148.1,141.7
XS GIS Cut Line= 2
     1742982.749      254930.392     1742724.123       255228.79
#Sta/Elev= 30
       0 1144.35     9.6 1140.39    19.3 1137.22    57.8 1124.74      77  1119.2
    86.7 1118.11    96.3 1116.33   115.6 1110.86   125.2  1108.6   134.8    1107
   144.5 1105.71   154.1 1104.85   163.7 1103.46     183 1098.42   191.5 1097.59
   202.2 1096.66   206.5 1097.01   211.9 1097.45   231.2 1104.32   240.8 1105.57
     260 1105.02   269.7 1105.28   288.9 1105.93   298.6 1106.64   308.2 1107.82
   317.8 1110.18   346.7 1120.31     366 1126.62   375.6  1128.7   394.9    1130
#Mann= 3 , 0 , 0
       0      .1       0   191.5    .045       0   206.5      .1       0
Bank Sta=191.5,206.5
XS Rating Curve= 0 ,0
Exp/Cntr=0.3,0.1

Type RM Length L Ch R = 1 ,23815   ,159.4,153.6,147.3
XS GIS Cut Line= 2
     1742827.049      254806.686     1742653.757      255158.424
#Sta/Elev= 30
       0  1138.8     9.8 1135.92    19.6 1133.85    29.4 1133.08      49 1126.37
    78.4 1115.11    88.2 1111.66      98 1109.12   107.8 1107.76   117.6 1107.16
   156.8 1101.89   176.4 1098.61   186.2 1096.44   194.1 1095.04   209.1 1093.87
   215.7 1093.34   225.5 1094.22   245.1  1100.7   254.9 1102.74   264.7 1103.15
   284.3 1102.08   294.1 1102.31   303.9 1103.52   323.5 1106.86   343.1 1110.59
   352.9 1113.09   362.7 1116.67   372.5 1119.25   382.3 1121.06   392.1 1124.88
#Mann= 3 , 0 , 0
       0      .1       0   194.1    .045       0   209.1      .1       0
Bank Sta=194.1,209.1
XS Rating Curve= 0 ,0
Exp/Cntr=0.3,0.1

Type RM Length L Ch R = 1 ,23661.4 ,162.3,157.1,151.8
XS GIS Cut Line= 3
      1742634.73      254756.045     1742554.178       255155.65
     1742553.733      255157.857
#Sta/Elev= 30
       0 1118.46     9.7 1115.04    19.4 1112.18    29.1 1109.83    48.5 1106.44
    58.2 1105.18    67.9 1104.93    87.4  1101.7    97.1 1100.62   135.9  1098.1
   155.3 1097.49   174.7  1096.2   184.4 1094.82   194.1 1092.48   203.8 1091.17
   204.7 1091.25   219.7 1092.61   232.9 1094.15   271.8 1102.84   281.5 1105.46
   291.2 1108.48   300.9 1111.01   310.6  1112.1   349.4 1128.38   368.8 1135.97
   378.5 1137.19   388.2 1137.01   397.9 1134.32   407.6 1133.11   409.9 1133.08
#Mann= 3 , 0 , 0
       0      .1       0   204.7    .045       0   219.7      .1       0
Bank Sta=204.7,219.7
XS Rating Curve= 0 ,0
Exp/Cntr=0.3,0.1

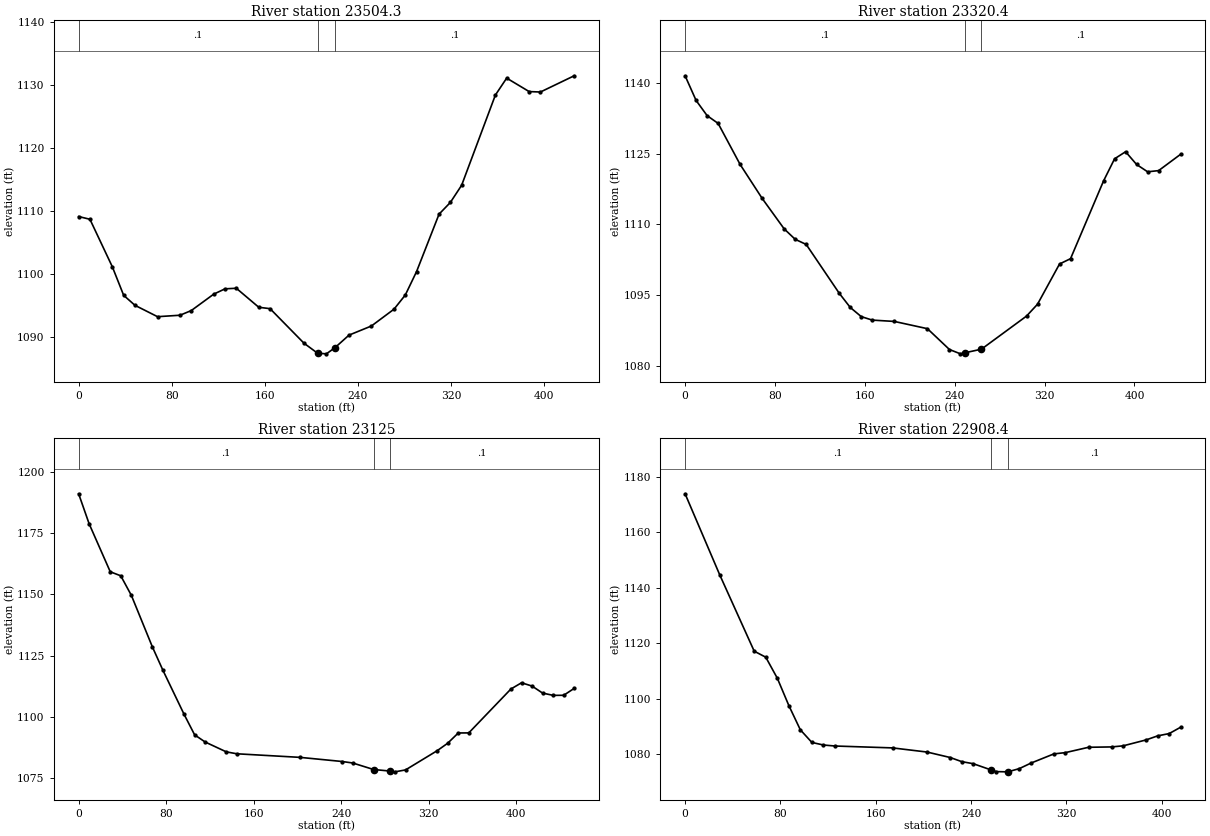
Type RM Length L Ch R = 1 ,23504.3 ,183.6,183.8,184
XS GIS Cut Line= 2
     1742430.565      254725.163      1742445.81      255150.741
#Sta/Elev= 30
       0 1109.13     9.7  1108.7      29 1101.16    38.7 1096.66    48.4 1095.08
    67.8 1093.28    87.1 1093.51    96.8 1094.25   116.1 1096.85   125.8 1097.69
   135.5 1097.78   154.8 1094.77   164.5 1094.55   193.6 1089.09   205.3  1087.5
   212.9  1087.4   220.3 1088.38   232.3 1090.36   251.6 1091.81     271 1094.47
   280.7 1096.71   290.4 1100.43   309.7 1109.51   319.4 1111.36   329.1 1114.08
   358.1 1128.36   367.8 1131.04   387.1 1128.91   396.8 1128.84   425.8 1131.41
#Mann= 3 , 0 , 0
       0      .1       0   205.3    .045       0   220.3      .1       0
Bank Sta=205.3,220.3
XS Rating Curve= 0 ,0
Exp/Cntr=0.3,0.1

Type RM Length L Ch R = 1 ,23320.4 ,192.1,194.9,197.8
XS GIS Cut Line= 2
     1742248.312      254697.595     1742260.783      255138.541
#Sta/Elev= 30
       0 1141.56     9.8 1136.32    19.6  1133.1    29.4 1131.45      49 1122.73
    68.6 1115.53    88.2 1109.06      98 1106.85   107.8 1105.76   137.2  1095.4
     147 1092.39   156.8 1090.44   166.6  1089.7   186.2 1089.42   215.7 1087.88
   235.3 1083.46   245.1 1082.54   248.8 1082.75   263.8 1083.53   303.9 1090.55
   313.7 1093.07   333.3 1101.61   343.1 1102.74   372.5 1119.25   382.3 1123.94
   392.1 1125.44   401.9 1122.73   411.7 1121.18   421.5 1121.43   441.1  1124.9
#Mann= 3 , 0 , 0
       0      .1       0   248.8    .045       0   263.8      .1       0
Bank Sta=248.8,263.8
XS Rating Curve= 0 ,0
Exp/Cntr=0.3,0.1

Type RM Length L Ch R = 1 ,23125   ,208.5,216.6,224.7
XS GIS Cut Line= 2
     1742090.758      254673.763     1742045.824      255124.368
#Sta/Elev= 30
       0 1190.96     9.6 1178.72    28.9 1159.17    38.5 1157.53    48.2 1149.54
    67.4 1128.54    77.1 1118.95    96.4 1101.03     106  1092.7   115.6 1089.79
   134.9 1085.78   144.5 1084.99   202.3 1083.53   240.9 1081.84   250.5 1081.23
   269.5 1078.58   284.5 1077.95     289 1077.63   298.7 1078.41   327.6 1086.24
   337.2 1089.28   346.9 1093.47   356.5  1093.5     395 1111.39   404.7 1113.93
   414.3 1112.59   423.9 1109.74   433.6  1108.8   443.2 1108.83   452.8 1111.64
#Mann= 3 , 0 , 0
       0      .1       0   269.5    .045       0   284.5      .1       0
Bank Sta=269.5,284.5
XS Rating Curve= 0 ,0
Exp/Cntr=0.3,0.1

Type RM Length L Ch R = 1 ,22908.4 ,234.5,237.5,240.6
XS GIS Cut Line= 2
     1741976.279      254641.426     1741792.457       255014.54
#Sta/Elev= 30
       0 1173.96      29 1144.77      58 1117.16    67.7 1114.99    77.4  1107.4
    87.1 1097.51    96.7  1088.8   106.4 1084.23   116.1  1083.3   125.8 1082.94
   174.1 1082.26   203.1 1080.76   222.5 1078.79   232.2  1077.3   241.8 1076.56
   256.4 1074.37   261.2  1073.7   270.8 1073.62   271.4 1073.69   280.5 1074.78
   290.2 1076.76   309.5 1080.09   319.2 1080.56   338.6 1082.48   357.9 1082.61
   367.6    1083   386.9 1085.14   396.6  1086.6   406.3 1087.43   415.9 1089.72
#Mann= 3 , 0 , 0
       0      .1       0   256.4    .045       0   271.4      .1       0
Bank Sta=256.4,271.4
XS Rating Curve= 0 ,0
Exp/Cntr=0.3,0.1