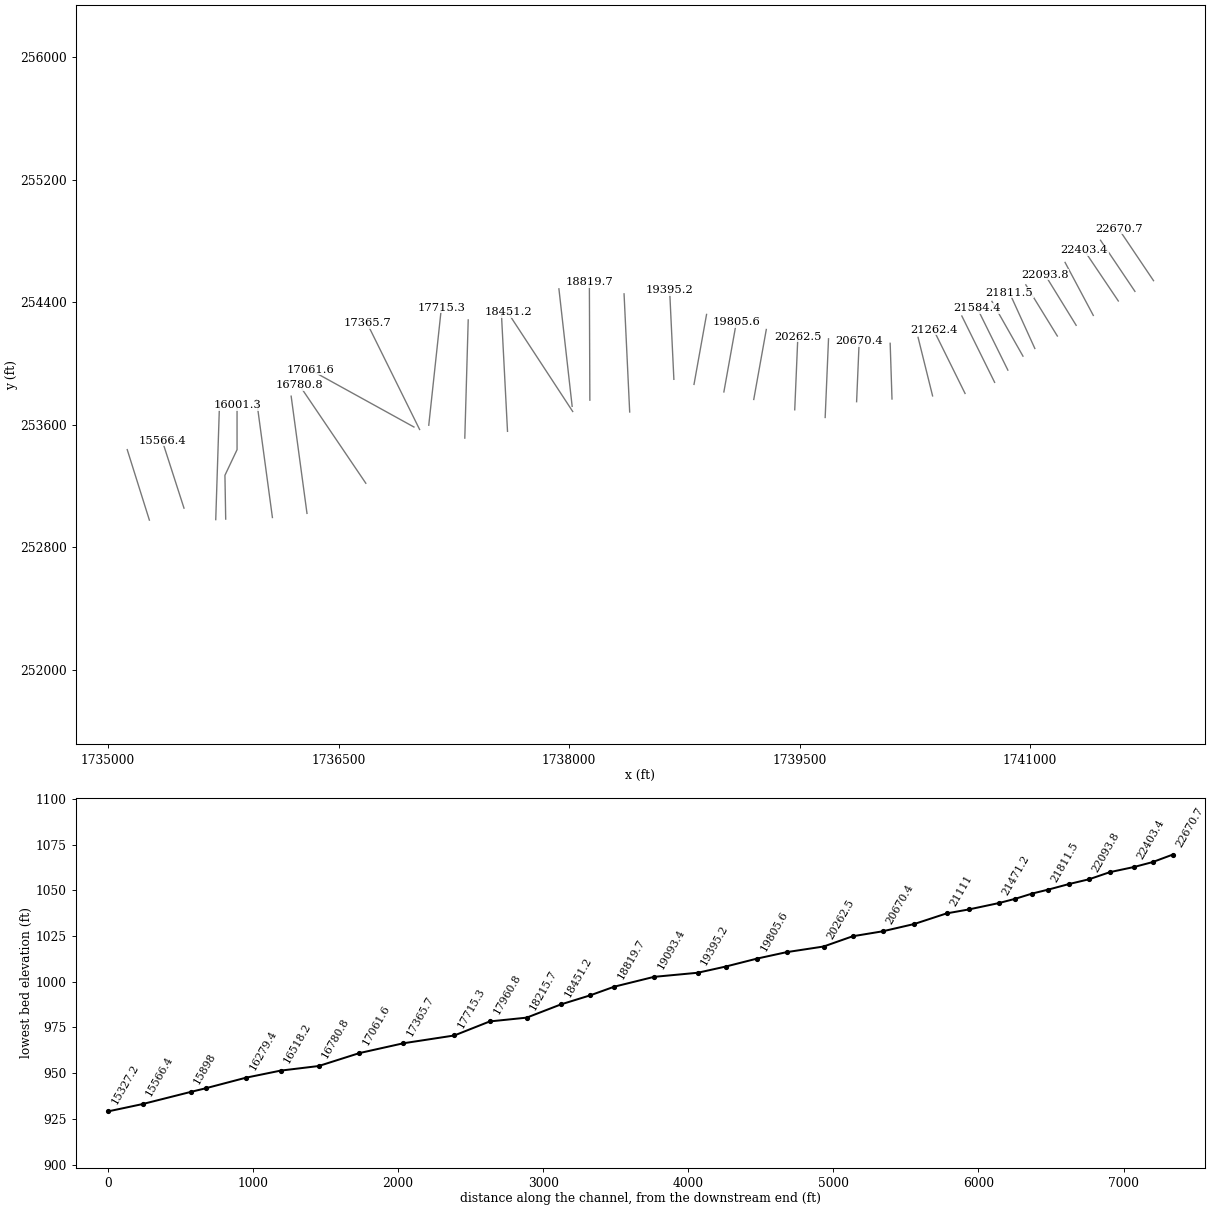
HEC-RAS study ELKCRK.prj: ELKCRK

--- ELKCRK.g01 (geometry) --- (continued)

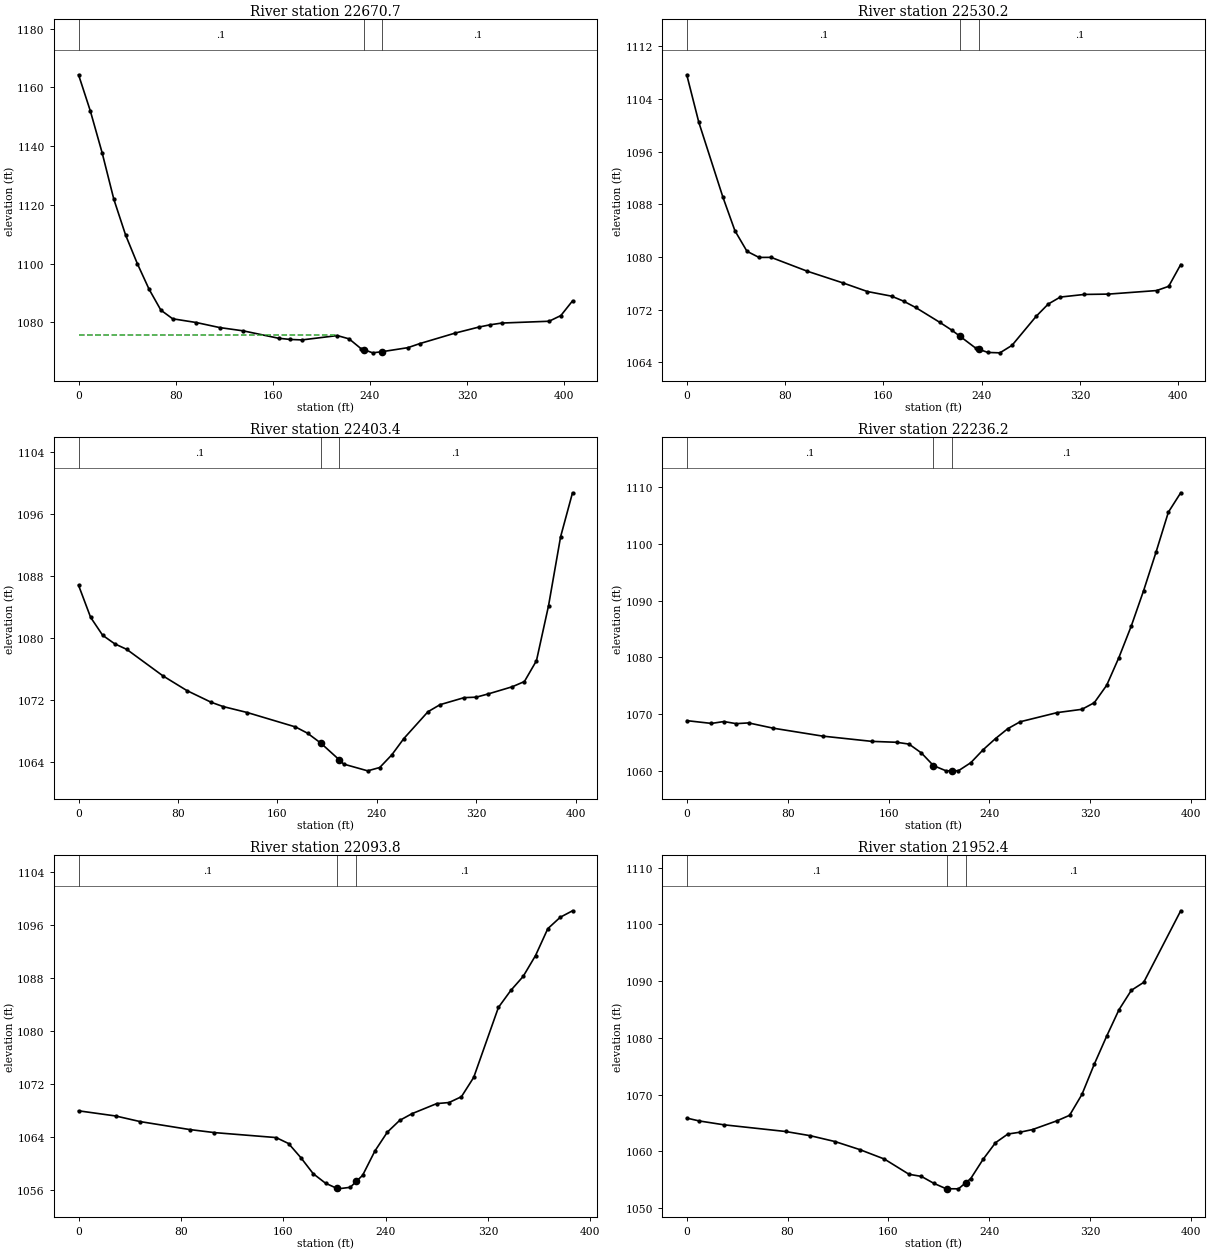
Type RM Length L Ch R = 1 ,22670.7 ,140.5,140.4,140.3
XS GIS Cut Line= 2
     1741802.303      254540.778     1741575.602      254878.601
#Sta/Elev= 30
       0 1164.31     9.7 1151.99    19.4 1137.77    29.1 1121.85    38.8 1109.67
    48.4 1099.99    58.1 1091.25    67.8 1084.14    77.5  1081.2    96.9 1079.93
   116.2 1078.21   135.6 1077.09   164.7 1074.57   174.4 1074.16     184    1074
   213.1 1075.48   222.8 1074.36   232.5 1071.07   235.1 1070.68   242.2  1069.6
   250.1    1070   271.2 1071.36   280.9 1072.73     310 1076.31   329.4 1078.35
     339 1079.16   348.7 1079.75   387.5 1080.36   397.2  1082.3   406.8 1087.29
#Mann= 3 , 0 , 0
       0      .1       0   235.1    .045       0   250.1      .1       0
#XS Ineff= 2 , 0
          212.58 1075.53
Permanent Ineff=
       F       F
Bank Sta=235.1,250.1
XS Rating Curve= 0 ,0
Exp/Cntr=0.3,0.1

Type RM Length L Ch R = 1 ,22530.2 ,126.8,126.9,127
XS GIS Cut Line= 2
     1741681.332      254470.795     1741457.394      254804.501
#Sta/Elev= 29
       0 1107.69     9.8 1100.48    29.4 1089.11    39.2    1084      49 1080.88
    58.8 1079.95    68.6 1079.96      98 1077.86   127.4 1076.06     147 1074.77
   166.6 1074.07   176.4 1073.31   186.2 1072.35   205.8  1070.1   215.6 1068.91
   222.5 1067.95   235.2 1066.16   237.5 1066.01     245 1065.52   254.8 1065.46
   264.6 1066.59   284.3 1071.01   294.1 1072.87   303.9 1073.93   323.5 1074.33
   343.1 1074.38   382.3 1074.92   392.1 1075.56   401.9 1078.87
#Mann= 3 , 0 , 0
       0      .1       0   222.5    .045       0   237.5      .1       0
Bank Sta=222.5,237.5
XS Rating Curve= 0 ,0
Exp/Cntr=0.3,0.1

Type RM Length L Ch R = 1 ,22403.4 ,169.6,167.2,164.9
XS GIS Cut Line= 2
     1741573.128      254408.197     1741351.662      254738.221
#Sta/Elev= 30
       0 1086.76     9.7 1082.62    19.4  1080.3    29.1  1079.2    38.8 1078.48
    67.9 1075.06    87.2 1073.16   106.6 1071.66   116.3  1071.1   135.7 1070.33
   174.5 1068.47   184.2 1067.66   194.9 1066.38   209.9  1064.2   213.3 1063.67
   232.6  1062.8   242.3 1063.23     252 1064.86   261.7 1066.97   281.1 1070.43
   290.8 1071.34   310.2 1072.25   319.9 1072.31   329.6 1072.73     349 1073.66
   358.7 1074.33   368.4 1077.02   378.1 1084.11   387.8 1093.01   397.4  1098.7
#Mann= 3 , 0 , 0
       0      .1       0   194.9    .045       0   209.9      .1       0
Bank Sta=194.9,209.9
XS Rating Curve= 0 ,0
Exp/Cntr=0.3,0.1

Type RM Length L Ch R = 1 ,22236.2 ,140.9,142.3,143.7
XS GIS Cut Line= 2
     1741410.334      254314.019     1741226.736      254659.909
#Sta/Elev= 30
       0 1068.83    19.6 1068.34    29.4 1068.67    39.2  1068.3      49 1068.43
    68.5  1067.5   107.7  1066.1   146.8 1065.17   166.4 1065.01   176.2 1064.69
     186 1063.13   195.6 1060.89   205.6 1059.97   210.6 1059.98   215.4 1059.99
   225.2 1061.41     235  1063.7   244.8 1065.67   254.5 1067.41   264.3 1068.63
   293.7 1070.25   313.3 1070.83   323.1    1072   332.9 1075.07   342.6 1079.97
   352.4 1085.53   362.2 1091.79     372 1098.55   381.8 1105.62   391.6 1109.05
#Mann= 3 , 0 , 0
       0      .1       0   195.6    .045       0   210.6      .1       0
Bank Sta=195.6,210.6
XS Rating Curve= 0 ,0
Exp/Cntr=0.3,0.1

Type RM Length L Ch R = 1 ,22093.8 ,141.4,141.4,141.4
XS GIS Cut Line= 2
      1741298.73      254249.455     1741096.839      254578.481
#Sta/Elev= 30
       0 1067.88      29  1067.1    48.2 1066.25    86.9 1065.05   106.2 1064.59
   154.4 1063.84   164.1 1062.94   173.7 1060.81   183.4 1058.38     193 1056.95
     202 1056.16   202.7  1056.1   212.3 1056.33     217 1057.21     222 1058.15
   231.6 1061.82   241.3 1064.66   250.9 1066.43   260.6 1067.45   279.9 1068.97
   289.5 1069.13   299.2 1070.01   308.8 1072.93   328.1 1083.49   337.8 1086.06
   347.4 1088.16   357.1 1091.32   366.7 1095.38   376.4  1097.1     386 1098.08
#Mann= 3 , 0 , 0
       0      .1       0     202    .045       0     217      .1       0
Bank Sta=202,217
XS Rating Curve= 0 ,0
Exp/Cntr=0.3,0.1

Type RM Length L Ch R = 1 ,21952.4 ,143.7,140.9,138.1
XS GIS Cut Line= 2
     1741176.394       254179.46      1740971.36      254513.607
#Sta/Elev= 30
       0 1065.88     9.8 1065.38    29.4  1064.7    78.4 1063.52      98 1062.78
   117.6 1061.75   137.2 1060.34   156.8 1058.67   176.4 1055.98   186.2 1055.61
     196  1054.4   205.8 1053.44   206.6 1053.44   215.6 1053.42   221.6 1054.53
   225.4 1055.24   235.2 1058.63     245 1061.54   254.8 1063.07   264.6  1063.4
   274.4 1063.86     294 1065.42   303.8 1066.37   313.6 1070.04   323.4 1075.37
   333.2 1080.29     343 1084.96   352.8 1088.38   362.6 1089.78     392 1102.39
#Mann= 3 , 0 , 0
       0      .1       0   206.6    .045       0   221.6      .1       0
Bank Sta=206.6,221.6
XS Rating Curve= 0 ,0
Exp/Cntr=0.3,0.1

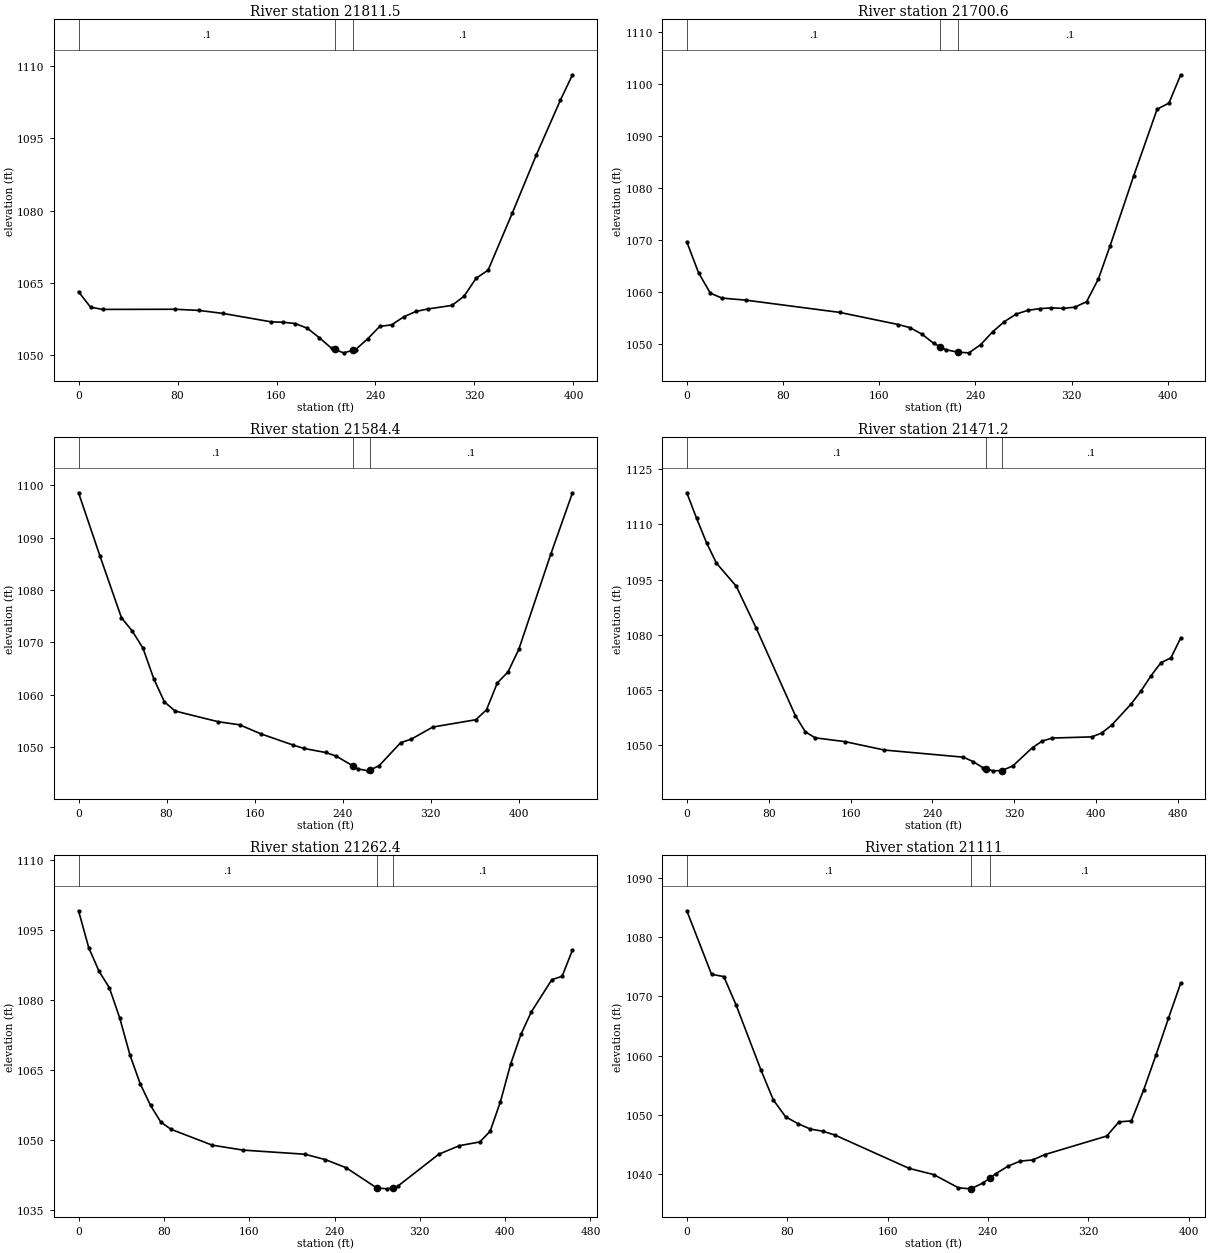
Type RM Length L Ch R = 1 ,21811.5 ,108.8,110.8,112.8
XS GIS Cut Line= 2
     1741030.016      254098.139     1740865.116      254461.666
#Sta/Elev= 30
       0 1063.12     9.7 1059.91    19.5 1059.45    77.9 1059.48    97.4 1059.24
   116.8 1058.61   155.8 1056.86   165.5 1056.78   175.2 1056.51     185 1055.52
   194.7 1053.54   204.5 1051.37   206.9 1051.13   214.2 1050.42   221.9 1050.95
   223.9 1051.09   233.7 1053.34   243.4 1055.91   253.1 1056.25   262.9 1057.91
   272.6 1059.02   282.4 1059.54   301.8 1060.28   311.6 1062.19   321.3 1065.92
     331 1067.61   350.5 1079.43     370 1091.58   389.4 1102.93   399.2 1108.23
#Mann= 3 , 0 , 0
       0      .1       0   206.9    .045       0   221.9      .1       0
Bank Sta=206.9,221.9
XS Rating Curve= 0 ,0
Exp/Cntr=0.3,0.1

Type RM Length L Ch R = 1 ,21700.6 ,117.5,116.2,114.9
XS GIS Cut Line= 2
     1740952.776      254048.107     1740750.672      254405.716
#Sta/Elev= 30
       0  1069.6     9.8 1063.64    19.6 1059.73    29.3 1058.79    48.9  1058.4
   127.1 1056.04     176  1053.7   185.8 1053.09   195.6 1051.85   205.4 1050.07
   210.6 1049.44   215.2 1048.88   225.6 1048.38   234.7 1048.26   244.5 1049.86
   254.3 1052.29   264.1 1054.26   273.8  1055.7   283.6 1056.43   293.4 1056.76
   303.2 1056.91     313 1056.81   322.8 1057.05   332.5  1058.1   342.3 1062.46
   352.1 1068.87   371.6 1082.24   391.2 1095.13     401 1096.29   410.8 1101.74
#Mann= 3 , 0 , 0
       0      .1       0   210.6    .045       0   225.6      .1       0
Bank Sta=210.6,225.6
XS Rating Curve= 0 ,0
Exp/Cntr=0.3,0.1

Type RM Length L Ch R = 1 ,21584.4 ,113,113.1,113.2
XS GIS Cut Line= 2
      1740854.39       253956.92     1740656.067      254359.464
#Sta/Elev= 30
       0  1098.6    19.5 1086.47      39 1074.69    48.8 1072.14    58.5  1068.9
    68.3 1063.05      78  1058.6    87.8 1056.84   126.8  1054.8   146.3 1054.21
   165.8 1052.47   195.1 1050.32   204.9 1049.68   224.4 1048.91   234.1 1048.22
   249.8 1046.28   253.6 1045.78   263.4  1045.4   264.8 1045.54   273.2  1046.4
   292.7 1050.79   302.4 1051.47   321.9 1053.78     361 1055.18   370.7 1057.08
   380.5 1062.21   390.2 1064.32     400 1068.62   429.2 1086.91   448.8 1098.58
#Mann= 3 , 0 , 0
       0      .1       0   249.8    .045       0   264.8      .1       0
Bank Sta=249.8,264.8
XS Rating Curve= 0 ,0
Exp/Cntr=0.3,0.1

Type RM Length L Ch R = 1 ,21471.2 ,209.1,209,208.9
XS GIS Cut Line= 2
     1740768.277      253877.108     1740554.981      254310.045
#Sta/Elev= 30
       0 1118.58     9.6 1111.62    19.3 1104.99      29 1099.45    48.3  1093.2
    67.6 1081.94   106.2 1057.99   115.8 1053.66   125.5 1052.02   154.4    1051
     193 1048.71   270.3 1046.77   279.9 1045.55   289.6 1043.87   292.8  1043.6
   299.2 1043.06   307.8 1043.13   318.5 1044.38   337.8 1049.38   347.5 1051.17
   357.1 1051.97   395.8 1052.28   405.4 1053.34   415.1 1055.46   434.4  1061.3
     444 1064.83   453.7 1068.94   463.3 1072.44     473 1073.73   482.6 1079.15
#Mann= 3 , 0 , 0
       0      .1       0   292.8    .045       0   307.8      .1       0
Bank Sta=292.8,307.8
XS Rating Curve= 0 ,0
Exp/Cntr=0.3,0.1

Type RM Length L Ch R = 1 ,21262.4 ,156.1,151.2,146.4
XS GIS Cut Line= 2
     1740575.804       253804.77     1740371.148       254220.17
#Sta/Elev= 30
       0 1099.14     9.6 1091.18    19.3 1086.14    28.9 1082.63    38.6 1076.17
    48.2 1068.23    57.9    1062    67.5 1057.42    77.2 1053.83    86.8 1052.29
   125.4  1048.9   154.4 1047.84   212.2 1046.96   231.5  1045.8   250.8 1044.07
   279.5 1039.75   289.4 1039.54   294.5 1039.82   299.1 1040.07   337.7 1046.95
     357 1048.79   376.2 1049.59   385.9 1051.87   395.6 1058.24   405.2 1066.33
   414.8 1072.65   424.5 1077.46   443.8 1084.38   453.4  1085.1   463.1 1090.72
#Mann= 3 , 0 , 0
       0      .1       0   279.5    .045       0   294.5      .1       0
Bank Sta=279.5,294.5
XS Rating Curve= 0 ,0
Exp/Cntr=0.3,0.1

Type RM Length L Ch R = 1 ,21111   ,227.9,223.2,218.4
XS GIS Cut Line= 2
     1740364.617      253788.649     1740270.108      254170.773
#Sta/Elev= 30
       0 1084.52    19.7 1073.76    29.5 1073.37    39.4 1068.49      59 1057.59
    68.9 1052.49    78.7 1049.62    88.6 1048.45    98.4 1047.54   108.2 1047.18
   118.1 1046.52   177.1 1040.88   196.8 1039.82   216.5 1037.58   226.3 1037.41
   226.5 1037.43   236.2 1038.42   241.5 1039.24     246 1039.94   255.9 1041.24
   265.7 1042.11   275.6  1042.3   285.4 1043.22   334.6 1046.35   344.4 1048.76
   354.3 1048.92   364.1 1054.18     374 1060.16   383.8 1066.29   393.6 1072.26
#Mann= 3 , 0 , 0
       0      .1       0   226.5    .045       0   241.5      .1       0
Bank Sta=226.5,241.5
XS Rating Curve= 0 ,0
Exp/Cntr=0.3,0.1

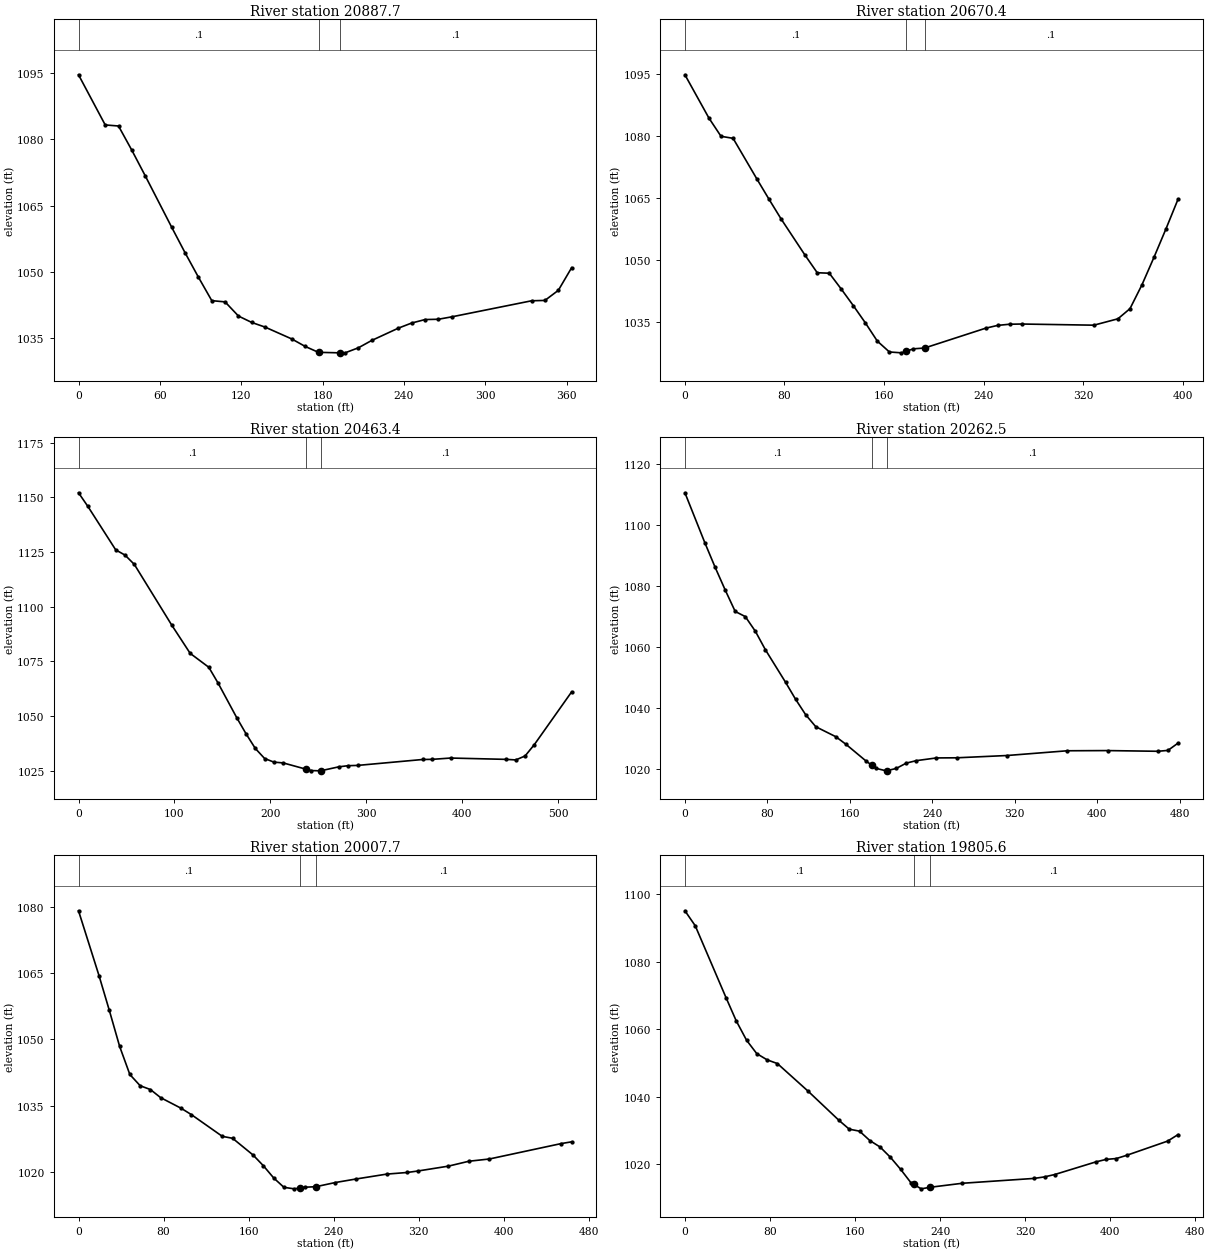
Type RM Length L Ch R = 1 ,20887.7 ,219,217.3,215.6
XS GIS Cut Line= 2
     1740100.487      253768.486     1740088.589      254131.993
#Sta/Elev= 30
       0 1094.68    19.7  1083.3    29.5 1083.06    39.3 1077.58    49.2 1071.77
    68.8 1060.05    78.6  1054.3    88.5 1048.73    98.3 1043.44   108.1 1043.16
     118 1039.94   127.8 1038.49   137.6 1037.44   157.3 1034.75   167.1 1033.07
   176.9 1031.72   177.7 1031.71   192.7  1031.6   196.6  1031.6   206.4 1032.74
   216.2  1034.4   235.9  1037.2   245.7 1038.36   255.6 1039.15   265.4 1039.22
   275.2 1039.76   334.2 1043.41     344 1043.49   353.9 1045.78   363.7 1050.91
#Mann= 3 , 0 , 0
       0      .1       0   177.7    .045       0   192.7      .1       0
Bank Sta=177.7,192.7
XS Rating Curve= 0 ,0
Exp/Cntr=0.3,0.1

Type RM Length L Ch R = 1 ,20670.4 ,206.8,206.8,206.8
XS GIS Cut Line= 2
     1739870.194      253750.906     1739887.023      254146.787
#Sta/Elev= 30
       0 1094.77    19.3 1084.31      29 1079.91    38.7 1079.42      58 1069.51
    67.6 1064.69    77.3 1059.94    96.6 1051.16   106.3 1046.96     116 1046.84
   125.6 1043.02   135.3 1039.01     145 1034.84   154.6 1030.44   164.3 1027.82
     174 1027.61   177.5 1027.96   183.6 1028.58   192.5 1028.77   241.6 1033.56
   251.3 1034.24   260.9 1034.52   270.6 1034.57   328.6 1034.29   347.9 1035.83
   357.6 1038.28   367.2 1044.03   376.9  1050.7   386.6 1057.62   396.2 1064.71
#Mann= 3 , 0 , 0
       0      .1       0   177.5    .045       0   192.5      .1       0
Bank Sta=177.5,192.5
XS Rating Curve= 0 ,0
Exp/Cntr=0.3,0.1

Type RM Length L Ch R = 1 ,20463.4 ,200.9,200.9,200.9
XS GIS Cut Line= 2
     1739665.635      253647.908     1739687.465      254161.433
#Sta/Elev= 30
       0 1152.05     9.7 1145.86    38.8 1125.93    48.5 1123.55    58.2 1119.29
      97 1091.66   116.4 1078.62   135.8 1072.26   145.5 1065.02   164.9 1049.23
   174.6 1041.87   184.3 1035.13     194 1030.54   203.7 1028.88   213.4 1028.52
   237.4 1025.62   242.4 1025.03   252.2  1024.9   252.4 1024.92   271.5 1026.75
   281.2 1027.26   290.9 1027.38   358.8 1030.09   368.5 1030.15   387.9 1030.75
   446.1 1030.14   455.8 1029.89   465.5  1031.7   475.2 1036.93     514    1061
#Mann= 3 , 0 , 0
       0      .1       0   237.4    .045       0   252.4      .1       0
Bank Sta=237.4,252.4
XS Rating Curve= 0 ,0
Exp/Cntr=0.3,0.1

Type RM Length L Ch R = 1 ,20262.5 ,257.8,254.7,251.6
XS GIS Cut Line= 2
     1739467.584      253698.003     1739487.907       254176.08
#Sta/Elev= 30
       0 1110.57    19.5 1094.03    29.3 1086.12    39.1 1078.64    48.8  1071.6
    58.6 1069.92    68.4 1065.08    78.1 1059.03    97.6 1048.39   107.4 1042.77
   117.2 1037.69     127 1033.76   146.5 1030.47   156.2 1028.01   175.8 1022.49
   181.2 1021.15   185.5 1020.09   195.3 1019.28   196.2 1019.35   205.1 1020.07
   214.8 1021.82   224.6 1022.63   244.1 1023.52   263.7 1023.56   312.5 1024.31
   371.1 1025.87   410.2 1025.93     459  1025.7   468.7 1025.99   478.5 1028.38
#Mann= 3 , 0 , 0
       0      .1       0   181.2    .045       0   196.2      .1       0
Bank Sta=181.2,196.2
XS Rating Curve= 0 ,0
Exp/Cntr=0.3,0.1

Type RM Length L Ch R = 1 ,20007.7 ,201.8,202.4,203
XS GIS Cut Line= 2
     1739200.913      253765.456     1739282.596      254222.187
#Sta/Elev= 30
       0 1079.08    19.3 1064.41      29 1056.55    38.7 1048.41    48.3 1042.06
      58 1039.52    67.7 1038.65    77.3 1036.82    96.7  1034.4   106.3 1032.97
   135.3 1028.07     145 1027.63   164.3 1023.84     174 1021.41   183.7 1018.65
   193.3 1016.54     203  1016.2   208.5  1016.4   212.7 1016.56   223.5 1016.69
   241.7 1017.63     261 1018.42     290 1019.53   309.3  1019.9     319 1020.22
     348 1021.33   367.3 1022.44   386.6 1022.95   454.3 1026.44     464 1026.83
#Mann= 3 , 0 , 0
       0      .1       0   208.5    .045       0   223.5      .1       0
Bank Sta=208.5,223.5
XS Rating Curve= 0 ,0
Exp/Cntr=0.3,0.1

Type RM Length L Ch R = 1 ,19805.6 ,216.4,215.8,215.1
XS GIS Cut Line= 2
     1739006.533      253814.622     1739088.206      254271.296
#Sta/Elev= 30
       0 1095.05     9.7 1090.62    38.7  1069.3    48.3 1062.43      58 1056.71
    67.6 1052.74    77.3 1050.91      87  1049.8     116 1041.59     145 1032.96
   154.6 1030.37   164.3 1029.78     174 1026.99   183.6 1025.09   193.3 1022.05
     203 1018.45   212.6 1014.52   215.3 1014.01   222.3  1012.7   230.3 1013.15
     261 1014.35   328.6 1015.79   338.3 1016.24   347.9 1016.94   386.6 1020.68
   396.3 1021.42   405.9 1021.68   415.6 1022.63   454.2 1026.85   463.9 1028.76
#Mann= 3 , 0 , 0
       0      .1       0   215.3    .045       0   230.3      .1       0
Bank Sta=215.3,230.3
XS Rating Curve= 0 ,0
Exp/Cntr=0.3,0.1

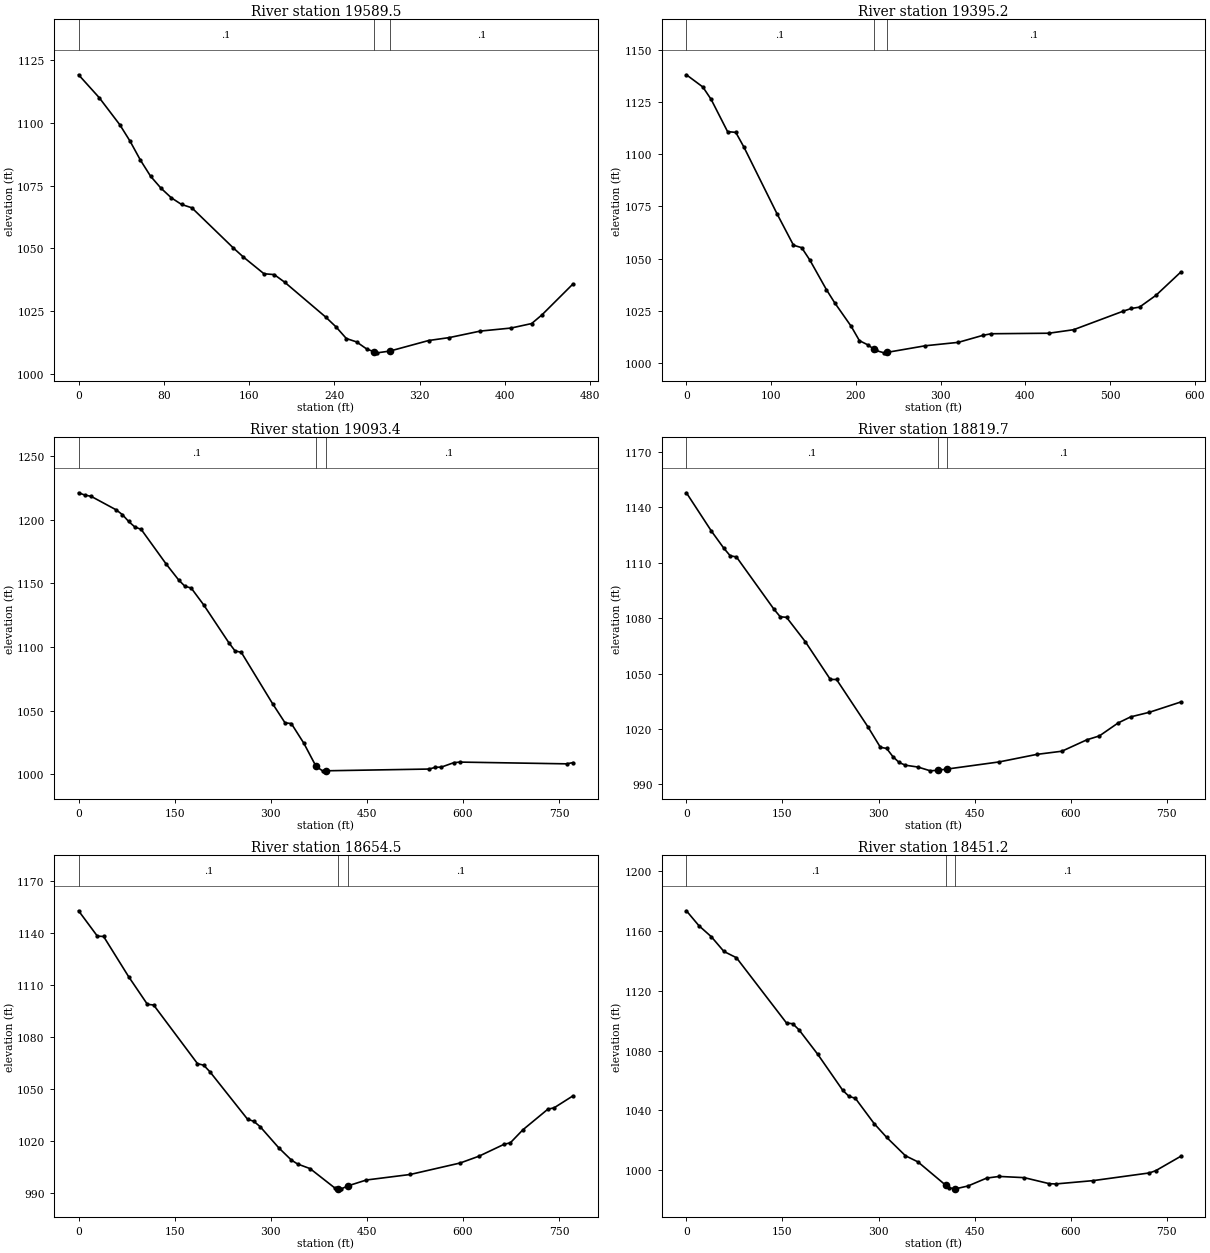
Type RM Length L Ch R = 1 ,19589.5 ,189.3,194.3,199.4
XS GIS Cut Line= 2
     1738812.153      253863.789     1738893.815      254320.405
#Sta/Elev= 30
       0 1119.25    19.3 1110.16    38.7 1099.32    48.3 1092.79      58 1085.24
    67.6 1078.78    77.3 1074.04      87  1070.2    96.6 1067.54   106.3  1066.2
     145 1050.28   154.6 1046.59     174 1039.89   183.6 1039.56   193.3 1036.57
   231.9 1022.63   241.6 1018.71   251.3 1014.06   260.9 1012.71   270.6 1009.83
   277.2 1008.81   280.2 1008.35   292.2 1009.06   328.6 1013.27   347.9 1014.43
   376.9 1017.02   405.9 1018.24   425.2 1020.03   434.9  1023.5   463.9 1035.78
#Mann= 3 , 0 , 0
       0      .1       0   277.2    .045       0   292.2      .1       0
Bank Sta=277.2,292.2
XS Rating Curve= 0 ,0
Exp/Cntr=0.3,0.1

Type RM Length L Ch R = 1 ,19395.2 ,301.5,301.5,301.4
XS GIS Cut Line= 2
     1738681.168      253896.921     1738653.493      254479.683
#Sta/Elev= 30
       0 1138.05    19.4 1132.21    29.2 1126.27    48.6 1110.84    58.3 1110.48
    68.1 1103.27     107 1071.47   126.4 1056.45   136.1 1055.27   145.8 1049.28
   165.3 1035.16     175 1028.91   194.5 1017.62   204.2 1010.76   213.9  1008.8
   221.5 1006.65   223.6 1006.06   233.4 1004.93   236.5 1005.13     282 1008.32
   320.9 1009.95     350 1013.31   359.8 1014.07   427.8 1014.32     457    1016
   515.4 1024.86   525.1 1026.16   534.8 1026.82   554.2 1032.46   583.4 1043.56
#Mann= 3 , 0 , 0
       0      .1       0   221.5    .045       0   236.5      .1       0
Bank Sta=221.5,236.5
XS Rating Curve= 0 ,0
Exp/Cntr=0.3,0.1

Type RM Length L Ch R = 1 ,19093.4 ,274.7,273.8,272.9
XS GIS Cut Line= 2
     1738393.594      253683.777      1738356.99      254454.551
#Sta/Elev= 30
       0 1221.22     9.8 1219.42    19.5 1218.45    58.6 1207.83    68.4 1204.06
    78.1 1198.72    87.9 1194.31    97.7 1192.48   136.8 1165.18   156.3 1152.67
     166 1147.75   175.8 1146.35   195.4 1133.05   234.4 1103.51   244.2 1096.96
     254 1095.83   302.8  1055.5   322.3  1040.4   332.1 1039.86   351.6  1024.4
   370.7 1006.18   380.9 1002.68   385.7 1002.71     547 1004.09   556.8 1005.43
   566.5 1005.65   586.1 1009.16   595.8 1009.55   761.9 1008.18   771.6 1009.14
#Mann= 3 , 0 , 0
       0      .1       0   370.7    .045       0   385.7      .1       0
Bank Sta=370.7,385.7
XS Rating Curve= 0 ,0
Exp/Cntr=0.3,0.1

Type RM Length L Ch R = 1 ,18819.7 ,162.4,164.8,167.4
XS GIS Cut Line= 2
     1738134.473      253760.888     1738131.263      254532.525
#Sta/Elev= 30
       0 1147.83    39.1 1127.06    58.6 1117.74    68.4 1113.72    78.1 1113.11
   136.8 1084.74   146.5 1080.71   156.3 1080.42   185.6 1067.24   224.7  1046.8
   234.4 1046.76   283.3 1021.16   302.8 1010.07   312.6 1009.43   322.3 1005.02
   332.1 1001.83   341.9 1000.35   361.4  999.37   380.9  997.31     392  997.62
     407  998.28   488.4 1002.15     547 1006.22   586.1 1007.93   625.1 1014.11
   644.7 1016.22     674 1023.25   693.5 1026.52   722.8 1029.02   771.6 1034.56
#Mann= 3 , 0 , 0
       0      .1       0     392    .045       0     407      .1       0
Bank Sta=392,407
XS Rating Curve= 0 ,0
Exp/Cntr=0.3,0.1

Type RM Length L Ch R = 1 ,18654.5 ,192.7,203.3,213.8
XS GIS Cut Line= 2
     1738019.241      253720.574      1737933.09      254487.393
#Sta/Elev= 30
       0 1152.69    29.3 1138.11    39.1 1137.89    78.1 1114.78   107.4 1098.85
   117.2 1098.43   185.6  1064.7   195.4 1063.76   205.1 1059.97   263.7 1032.72
   273.5 1031.47   283.3 1028.45   312.6 1016.18   332.1 1009.19   341.9  1006.9
   361.4 1004.24   400.5  992.95   405.4  992.77   410.2   992.6   420.4  994.31
   449.3  997.69   517.7 1000.87   595.8 1007.49   625.1 1011.41   664.2 1018.24
     674 1019.11   693.5 1026.57   732.6 1038.47   742.3 1039.25   771.6  1046.1
#Mann= 3 , 0 , 0
       0      .1       0   405.4    .045       0   420.4      .1       0
Bank Sta=405.4,420.4
XS Rating Curve= 0 ,0
Exp/Cntr=0.3,0.1

Type RM Length L Ch R = 1 ,18451.2 ,247.6,235.6,223.5
XS GIS Cut Line= 2
     1738022.779      253686.961      1737600.97      254333.112
#Sta/Elev= 30
       0  1173.5    19.5 1163.55    39.1 1156.07    58.6  1146.3    78.1 1142.12
   156.3 1098.46     166 1097.98   175.8  1093.9   205.1 1077.52   244.2 1053.39
     254 1049.38   263.7 1048.16     293 1031.27   312.6 1022.01   341.9 1009.73
   361.4 1005.63   404.5  990.12   410.2  988.25   419.5  987.63     420   987.6
   439.5   989.5   468.8   994.8   488.4  995.89   527.4  995.08   566.5  991.05
   576.3  990.86   634.9  993.09   722.8  998.24   732.6  999.73   771.6 1009.34
#Mann= 3 , 0 , 0
       0      .1       0   404.5    .045       0   419.5      .1       0
Bank Sta=404.5,419.5
XS Rating Curve= 0 ,0
Exp/Cntr=0.3,0.1

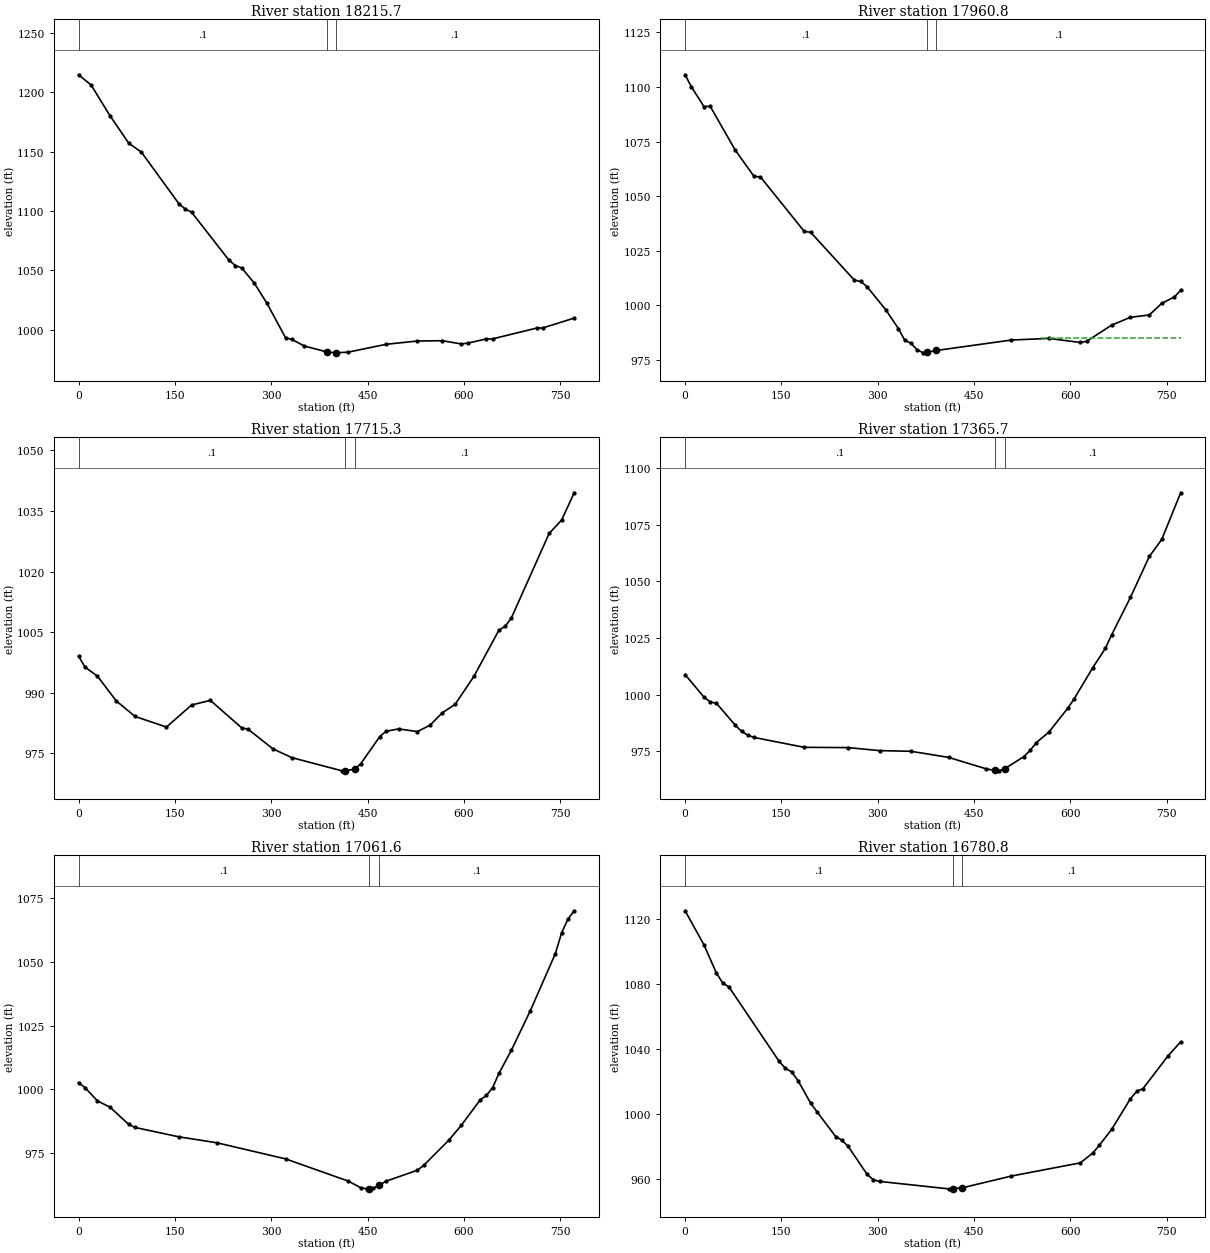
Type RM Length L Ch R = 1 ,18215.7 ,255.9,254.3,252.8
XS GIS Cut Line= 2
     1737598.599      253557.573      1737558.78      254328.189
#Sta/Elev= 30
       0  1214.8    19.5  1206.1    48.8 1180.33    78.1 1157.05    97.7 1149.61
   156.3 1105.96     166 1101.66   175.8 1098.99   234.4 1058.28   244.2 1053.91
     254 1051.94   273.5 1039.17     293 1022.34   322.3     993   332.1  991.64
   351.6  986.08   386.3  981.19   400.5  980.37   401.3  980.38     420  980.98
   478.6  987.55   527.4  990.34   566.5  990.58   595.8  987.88   605.6  988.48
   634.9  992.11   644.7  992.16     713 1001.23   722.8 1001.39   771.6 1009.64
#Mann= 3 , 0 , 0
       0      .1       0   386.3    .045       0   401.3      .1       0
Bank Sta=386.3,401.3
XS Rating Curve= 0 ,0
Exp/Cntr=0.3,0.1

Type RM Length L Ch R = 1 ,17960.8 ,244.4,244.6,244.7
XS GIS Cut Line= 2
     1737320.689      253513.266     1737342.906       254284.59
#Sta/Elev= 30
       0 1105.59     9.8 1100.06    29.3 1091.06    39.1 1091.13    78.1  1071.1
   107.4 1059.04   117.2 1058.87   185.6 1033.87   195.4 1033.52   263.7 1011.54
   273.5 1010.97   283.3 1008.58   312.6  997.96   332.1  989.41   341.9  984.12
   351.6  982.72   361.4  979.64   371.2   978.3   376.3  978.53   391.3  979.38
   507.9  984.16   566.5   984.9   615.4  983.05   625.1  983.56   664.2  990.98
   693.5  994.58   722.8  995.63   742.3 1000.97   761.9  1003.9   771.6  1006.9
#Mann= 3 , 0 , 0
       0      .1       0   376.3    .045       0   391.3      .1       0
#XS Ineff= 2 , 0
                          556.24          984.97
Permanent Ineff=
       F       F
Bank Sta=376.3,391.3
XS Rating Curve= 0 ,0
Exp/Cntr=0.3,0.1

Type RM Length L Ch R = 1 ,17715.3 ,339.3,350.2,361.1
XS GIS Cut Line= 2
     1737086.191      253597.365     1737168.441      254364.612
#Sta/Elev= 30
       0  999.02     9.8  996.34    29.3  994.07    58.6  987.94    87.9  984.08
   136.8  981.46   175.8  986.92   205.1  988.08     254  981.24   263.7  980.94
   302.8  976.03   332.1  973.88   410.2  970.61   415.2  970.62   430.2  971.04
   439.5  972.41   468.8  979.08   478.6   980.4   498.2     981   527.4  980.34
     547   981.9   566.5  985.02   586.1  987.06   615.4  993.99   654.4 1005.46
   664.2 1006.42     674 1008.57   732.6 1029.42   752.1 1032.76   771.6 1039.51
#Mann= 3 , 0 , 0
       0      .1       0   415.2    .045       0   430.2      .1       0
Bank Sta=415.2,430.2
XS Rating Curve= 0 ,0
Exp/Cntr=0.3,0.1

Type RM Length L Ch R = 1 ,17365.7 ,290.4,304.2,317.9
XS GIS Cut Line= 2
     1737026.598      253569.457     1736685.573      254261.653
#Sta/Elev= 30
       0 1008.85    29.3  998.92    39.1  996.75    48.8  996.17    78.1  986.52
    87.9  983.79    97.7  982.08   107.4  981.09   185.6  976.74     254  976.61
   302.8  975.28   351.6  974.99   410.2   972.3   468.8  967.25   482.4  966.53
   488.4  966.36   497.4  967.21   527.4  972.64   537.2  975.37     547  978.84
   566.5  983.46   595.8  993.98   605.6  998.04   634.9 1011.95   654.4 1020.43
   664.2 1026.41   693.5 1042.93   722.8 1060.95   742.3 1068.52   771.6 1089.07
#Mann= 3 , 0 , 0
       0      .1       0   482.4    .045       0   497.4      .1       0
Bank Sta=482.4,497.4
XS Rating Curve= 0 ,0
Exp/Cntr=0.3,0.1

Type RM Length L Ch R = 1 ,17061.6 ,291.7,280.1,268.5
XS GIS Cut Line= 2
     1736989.662      253585.685     1736314.437      253959.189
#Sta/Elev= 30
       0  1002.6     9.8 1000.68    29.3  995.46    48.8     993    78.1   986.2
    87.9  985.03   156.3  981.35   214.9  979.05   322.3  972.71     420  963.99
   439.5  961.38   449.3  960.97   452.8  961.08   459.1  961.27   467.8  962.36
   478.6  963.96   527.4  968.25   537.2  970.15   576.3  980.01   595.8  985.87
   625.1  995.78   634.9  997.58   644.7 1000.69   654.4  1006.2     674 1015.42
   703.3 1030.78   742.3 1053.21   752.1 1061.39   761.9 1066.72   771.6 1069.99
#Mann= 3 , 0 , 0
       0      .1       0   452.8    .045       0   467.8      .1       0
Bank Sta=452.8,467.8
XS Rating Curve= 0 ,0
Exp/Cntr=0.3,0.1

Type RM Length L Ch R = 1 ,16780.8 ,271.9,263,254.2
XS GIS Cut Line= 2
      1736676.61      253218.549     1736244.897      253858.124
#Sta/Elev= 30
       0 1124.76    29.3 1103.89    48.8 1086.44    58.6 1080.41    68.4 1077.89
   146.5 1032.19   156.3  1027.9     166 1025.74   175.8 1020.42   195.4 1006.62
   205.1  1001.4   234.4  986.06   244.2  983.76     254  979.95   283.3  962.85
     293  959.48   302.8  958.46   410.2   953.9   416.9     954   431.9  954.55
   507.9  961.75   615.4  969.86   634.9  975.93   644.7  980.55   664.2  990.44
   693.5 1009.34   703.3 1013.78     713 1015.47   752.1 1035.66   771.6 1044.19
#Mann= 3 , 0 , 0
       0      .1       0   416.9    .045       0   431.9      .1       0
Bank Sta=416.9,431.9
XS Rating Curve= 0 ,0
Exp/Cntr=0.3,0.1

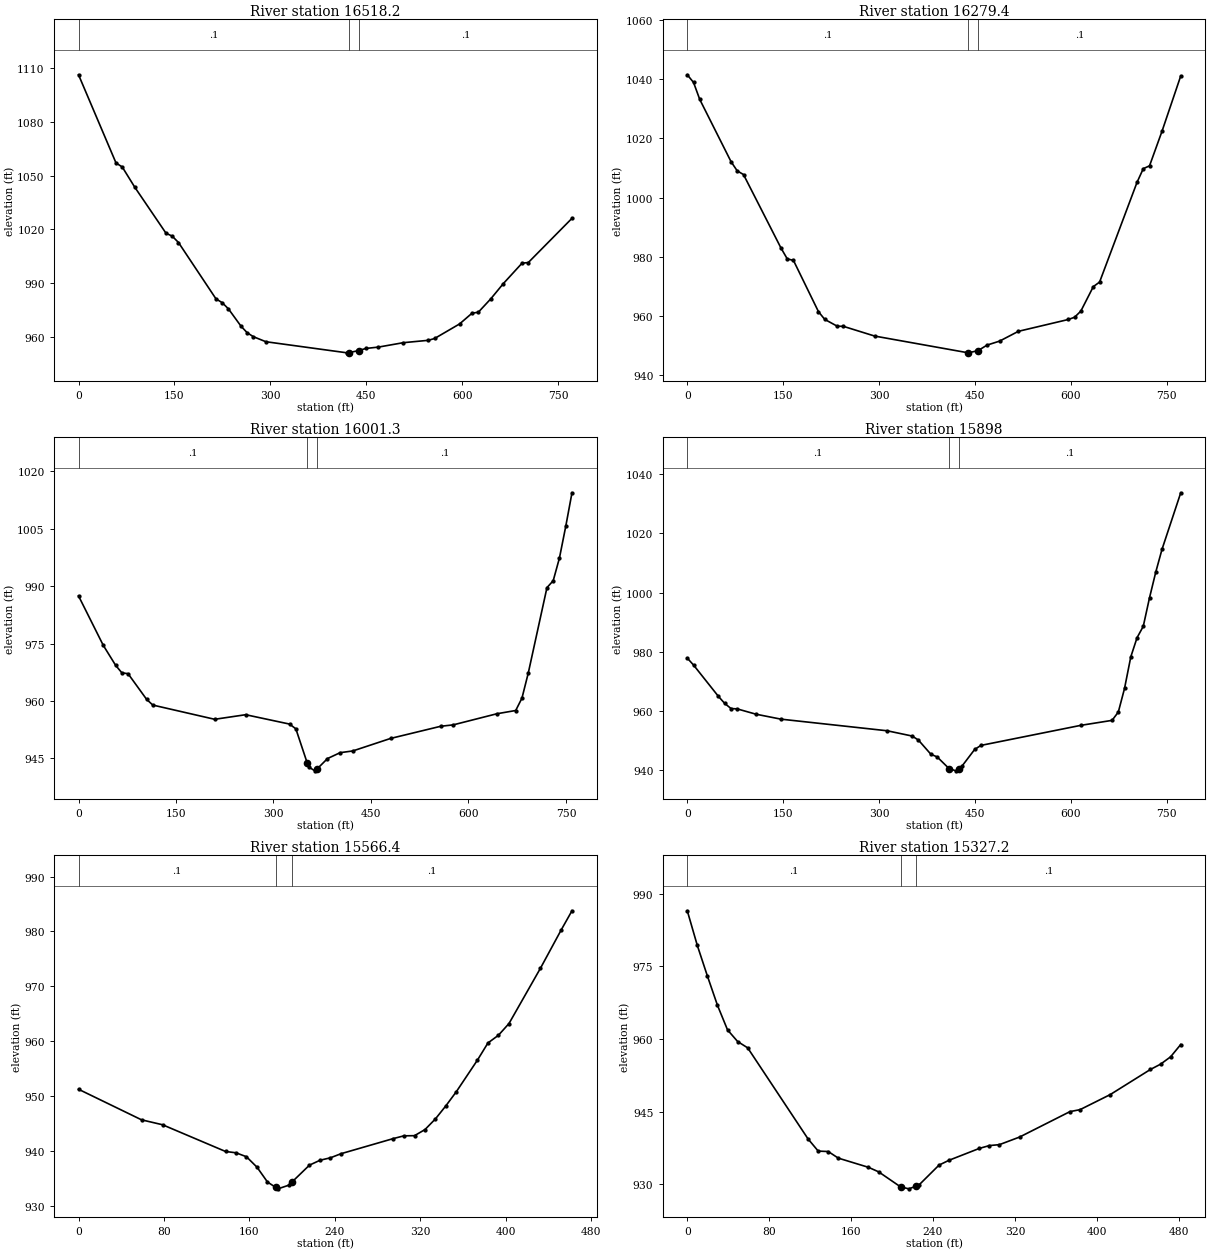
Type RM Length L Ch R = 1 ,16518.2 ,241,238.5,236
XS GIS Cut Line= 2
     1736293.764      253022.054     1736190.762      253786.792
#Sta/Elev= 30
       0 1106.04    58.6    1057    68.4 1054.74    87.9 1043.53   136.8 1017.91
   146.5 1016.29   156.3 1012.75   214.9  981.42   224.7  979.27   234.4  975.84
     254  966.24   263.7  962.57   273.5  960.34     293  957.56     420  951.38
   423.5  951.53   438.5  952.68   449.3  953.82   468.8  954.57   507.9  957.03
     547  958.35   556.8  959.36   595.8  967.45   615.4  973.45   625.1  973.95
   644.7  981.45   664.2  989.87   693.5 1001.25   703.3  1001.6   771.6  1026.2
#Mann= 3 , 0 , 0
       0      .1       0   423.5    .045       0   438.5      .1       0
Bank Sta=423.5,438.5
XS Rating Curve= 0 ,0
Exp/Cntr=0.3,0.1

Type RM Length L Ch R = 1 ,16279.4 ,288.6,278.1,267.5
XS GIS Cut Line= 2
     1736068.785      252995.024     1735965.782      253759.762
#Sta/Elev= 30
       0 1041.49     9.8 1038.89    19.5 1033.15    68.4 1012.13    78.1 1009.01
    87.9 1007.77   146.5  982.94   156.3  979.27     166  978.75   205.1  961.43
   214.9  958.82   234.4  956.52   244.2  956.46     293  953.18   439.5  947.51
   439.7  947.51   454.7  948.27   468.8  950.13   488.4  951.48   517.7  954.78
   595.8  958.78   605.6  959.54   615.4  961.62   634.9  969.89   644.7  971.43
   703.3 1005.17     713 1009.75   722.8 1010.72   742.3  1022.4   771.6  1041.1
#Mann= 3 , 0 , 0
       0      .1       0   439.7    .045       0   454.7      .1       0
Bank Sta=439.7,454.7
XS Rating Curve= 0 ,0
Exp/Cntr=0.3,0.1

Type RM Length L Ch R = 1 ,16001.3 ,94.3,103,111.7
XS GIS Cut Line= 4
     1735764.805      252984.766      1735759.84      253270.461
      1735838.76      253437.684     1735838.688      253726.331
#Sta/Elev= 30
       0  987.46    38.1  974.52    57.2  969.28    66.7  967.34    76.2  967.12
   104.8   960.4   114.3  958.91   209.5  955.19   257.2  956.39   324.7  953.94
   334.4   952.7     352  943.71   353.9  942.77   363.6  941.71     367  942.19
   383.1  944.92   402.5  946.46     422  946.91   480.3  950.19   557.2  953.36
   576.5  953.73   643.8  956.64   672.7  957.49   682.3  960.71     692  967.26
   720.8  989.63   730.4  991.43     740  997.36   749.7 1005.64   759.3 1014.43
#Mann= 3 , 0 , 0
       0      .1       0     352    .045       0     367      .1       0
Bank Sta=352,367
XS Rating Curve= 0 ,0
Exp/Cntr=0.3,0.1

Type RM Length L Ch R = 1 ,15898   ,323.4,331.2,339.1
XS GIS Cut Line= 2
      1735700.02      252981.161     1735724.992        253752.4
#Sta/Elev= 30
       0  977.85     9.8   975.5    48.8  964.87    58.6  962.51    68.4  960.79
    78.1  960.67   107.4  958.88   146.5   957.2   312.6  953.27   351.6  951.49
   361.4  950.13   380.9  945.33   390.7  944.43   409.2  940.51     420  939.72
   424.2  940.44   429.8  941.39   449.3  946.94   459.1  948.32   615.4  955.11
   664.2  956.79     674  959.61   683.7  967.59   693.5  978.28   703.3  984.76
     713   988.6   722.8  998.29   732.6 1006.99   742.3 1014.64   771.6 1033.77
#Mann= 3 , 0 , 0
       0      .1       0   409.2    .045       0   424.2      .1       0
Bank Sta=409.2,424.2
XS Rating Curve= 0 ,0
Exp/Cntr=0.3,0.1

Type RM Length L Ch R = 1 ,15566.4 ,239.5,239.3,239.1
XS GIS Cut Line= 2
     1735493.442      253056.108     1735351.946      253496.082
#Sta/Elev= 30
       0  951.24      59  945.67    78.7  944.77   137.7   939.9   147.5  939.66
   157.3  938.94   167.2  937.03     177  934.33   184.6  933.37   186.8  933.09
   196.7  933.74   199.6  934.27   216.3  937.41   226.2   938.3     236  938.75
   245.8  939.49     295  942.26   304.8  942.75   314.7  942.78   324.5  943.89
   334.3  945.84   344.2  948.25     354  950.83   373.7  956.57   383.5  959.68
   393.3  961.08   403.2  963.22   432.7  973.31   452.3  980.35   462.2  983.77
#Mann= 3 , 0 , 0
       0      .1       0   184.6    .045       0   199.6      .1       0
Bank Sta=184.6,199.6
XS Rating Curve= 0 ,0
Exp/Cntr=0.3,0.1

Type RM Length L Ch R = 1 ,15327.2 ,234.7,233.7,232.8
XS GIS Cut Line= 2
     1735268.174      252978.045     1735124.075      253437.956
#Sta/Elev= 30
       0  986.44     9.8  979.28    19.7  972.94    29.5  966.92    39.3  961.86
    49.2  959.45      59  958.15     118  939.34   127.9  936.84   137.7  936.75
   147.5  935.39     177  933.49   186.9  932.56   208.3  929.46   216.4  929.05
   223.3  929.59   226.2  929.82   245.9  933.95   255.7  934.95   285.2  937.39
   295.1  937.98   304.9  938.17   324.6  939.74   373.8  944.99   383.6  945.39
   413.1   948.5   452.4  953.69   462.3  954.78   472.1   956.3     482  958.84
#Mann= 3 , 0 , 0
       0      .1       0   208.3    .045       0   223.3      .1       0
Bank Sta=208.3,223.3
XS Rating Curve= 0 ,0
Exp/Cntr=0.3,0.1