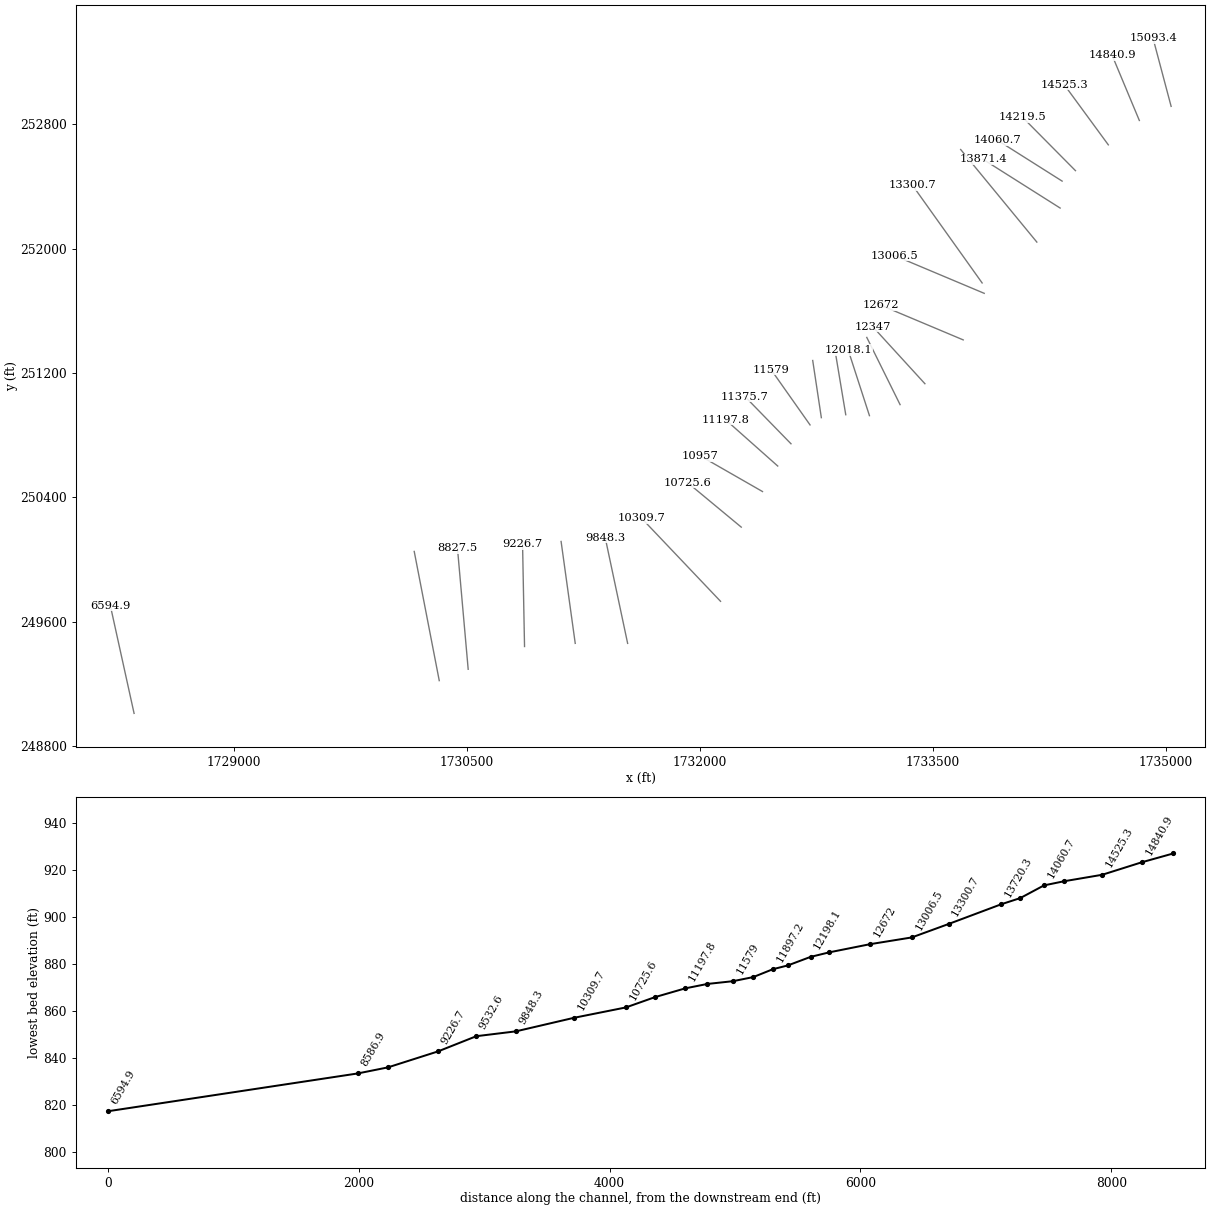
HEC-RAS study ELKCRK.prj: ELKCRK

--- ELKCRK.g01 (geometry) --- (continued)

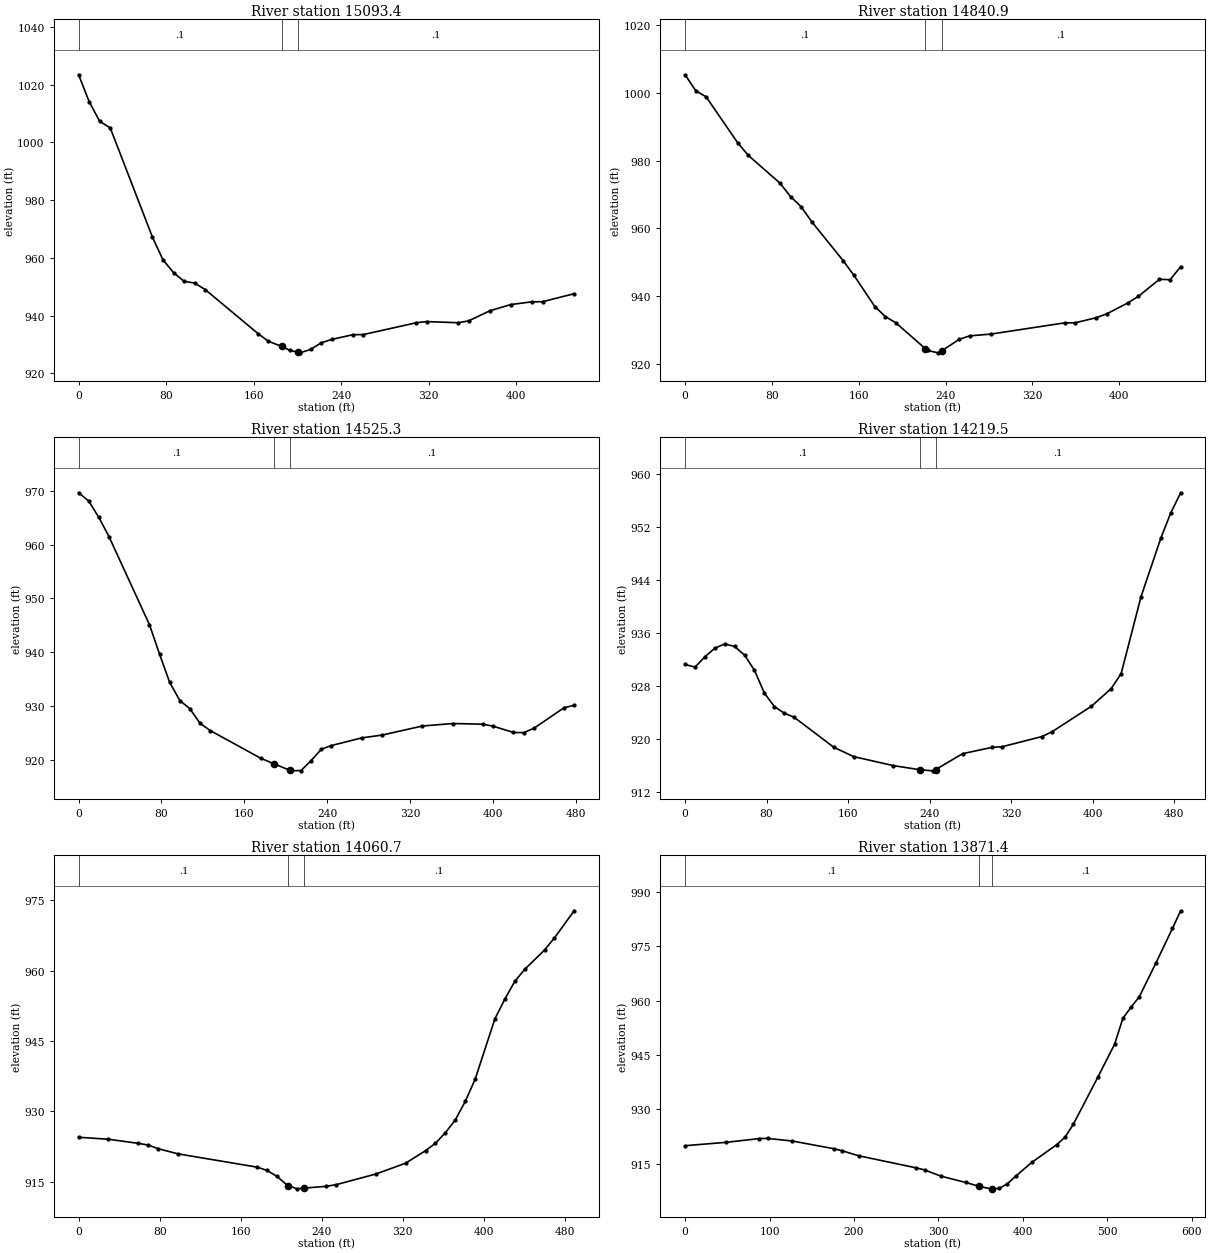
Type RM Length L Ch R = 1 ,15093.4 ,249.4,252.4,255.5
XS GIS Cut Line= 2
     1735034.328      252916.144     1734917.986      253353.994
#Sta/Elev= 30
       0 1023.47     9.6 1014.17    19.3 1007.32    28.9 1005.06    67.5  967.16
    77.1  959.31    86.8  954.88    96.4  951.86     106  951.28   115.7  949.02
   163.9  933.78   173.5  931.09   185.8  929.28   192.8     928   200.8  927.23
   202.4  927.08   212.1  928.27   221.7  930.54   231.3  931.73   250.6  933.36
   260.3  933.41   308.4  937.49   318.1  937.92     347  937.51   356.6  938.17
   375.9  941.66   395.2  943.83   414.5  944.77   424.1   944.8     453  947.58
#Mann= 3 , 0 , 0
       0      .1       0   185.8    .045       0   200.8      .1       0
Bank Sta=185.8,200.8
XS Rating Curve= 0 ,0
Exp/Cntr=0.3,0.1

Type RM Length L Ch R = 1 ,14840.9 ,310.1,315.5,320.8
XS GIS Cut Line= 2
     1734829.798      252825.182      1734653.91      253246.407
#Sta/Elev= 30
       0 1005.27     9.7 1000.62    19.4  998.75    48.6  985.16    58.3  981.48
    87.4  973.33    97.1  969.39   106.8  966.42   116.6  961.98   145.7  950.45
   155.4  946.21   174.8  936.95   184.5     934   194.2  932.15   221.3  924.54
   223.4     924   233.1  923.31   236.3  923.87   252.5  927.28   262.2  928.32
   281.6  928.83   349.6  932.14   359.4  932.17   378.8  933.67   388.5  934.82
   407.9  938.02   417.6  939.98     437  944.99   446.8  944.87   456.5  948.69
#Mann= 3 , 0 , 0
       0      .1       0   221.3    .045       0   236.3      .1       0
Bank Sta=221.3,236.3
XS Rating Curve= 0 ,0
Exp/Cntr=0.3,0.1

Type RM Length L Ch R = 1 ,14525.3 ,302.3,305.7,309
XS GIS Cut Line= 2
     1734630.132      252668.455     1734347.218      253054.385
#Sta/Elev= 30
       0  969.63     9.8  968.09    19.5  965.06    29.3  961.49    68.4  945.13
    78.1  939.69    87.9  934.42    97.7  931.05   107.4  929.53   117.2  926.83
     127  925.48   175.8  920.33   188.8  919.28   203.8  918.11   205.1  917.99
   214.8  918.05   224.6  919.91   234.4  922.01   244.1  922.69   273.4  924.11
     293  924.63     332  926.32   361.3  926.78   390.6  926.65   400.4  926.27
   419.9  925.12   429.7  925.08   439.5  925.88   468.8  929.72   478.5  930.15
#Mann= 3 , 0 , 0
       0      .1       0   188.8    .045       0   203.8      .1       0
Bank Sta=188.8,203.8
XS Rating Curve= 0 ,0
Exp/Cntr=0.3,0.1

Type RM Length L Ch R = 1 ,14219.5 ,153.6,158.8,164.9
XS GIS Cut Line= 2
     1734418.602      252502.415     1734076.175      252847.876
#Sta/Elev= 30
       0  931.27     9.7  930.86    19.5  932.44    29.2  933.72    38.9  934.37
    48.6  933.98    58.4  932.68    68.1  930.38    77.8  926.96    87.6  924.92
    97.3  923.92     107  923.31   145.9  918.78   165.4  917.37   204.3  916.01
   230.8  915.38   243.2  915.22   245.8   915.4   272.4  917.81   301.6  918.77
   311.3  918.86   350.2  920.39     360   921.1   398.9  924.97   418.3  927.64
     428  929.89   447.5  941.49     467  950.34   476.7  954.13   486.4  957.17
#Mann= 3 , 0 , 0
       0      .1       0   230.8    .045       0   245.8      .1       0
Bank Sta=230.8,245.8
XS Rating Curve= 0 ,0
Exp/Cntr=0.3,0.1

Type RM Length L Ch R = 1 ,14060.7 ,184.8,189.3,190.7
XS GIS Cut Line= 2
      1734332.78      252435.049     1733919.124      252696.674
#Sta/Elev= 30
       0  924.47    29.4  924.05    58.7  923.18    68.5  922.82    78.3  922.05
    97.9  920.94   176.2   918.1     186  917.41   195.8  916.14   205.6  914.32
   207.2  914.18   215.4  913.47   222.2  913.62   244.7  914.01   254.5  914.37
   293.7  916.64     323  918.95   342.6  921.61   352.4  923.19   362.2  925.44
     372  928.16   381.8   932.1   391.6  936.86   411.1  949.73   420.9  953.93
   430.7   957.7   440.5  960.28   460.1   964.4   469.9  966.99   489.4  972.78
#Mann= 3 , 0 , 0
       0      .1       0   207.2    .045       0   222.2      .1       0
Bank Sta=207.2,222.2
XS Rating Curve= 0 ,0
Exp/Cntr=0.3,0.1

Type RM Length L Ch R = 1 ,13871.4 ,158.3,150.9,143.6
XS GIS Cut Line= 2
     1734320.019      252261.667     1733824.135      252575.299
#Sta/Elev= 30
       0  919.97    48.9  920.91      88  921.94    97.8  921.98   127.1  921.26
     176  919.14   185.8  918.58   205.4   917.2   273.8  913.85   283.6  913.28
   303.2  911.55   332.5  909.82   348.1  908.75   361.8  908.07   363.1  908.08
   371.6  908.18   381.4  909.43   391.2  911.52   410.7  915.41   440.1  920.27
   449.8  922.32   459.6  925.86     489  939.03   508.5  947.96   518.3   955.1
   528.1  958.23   537.8  961.08   557.4  970.37     577  979.92   586.7  984.79
#Mann= 3 , 0 , 0
       0      .1       0   348.1    .045       0   363.1      .1       0
Bank Sta=348.1,363.1
XS Rating Curve= 0 ,0
Exp/Cntr=0.3,0.1

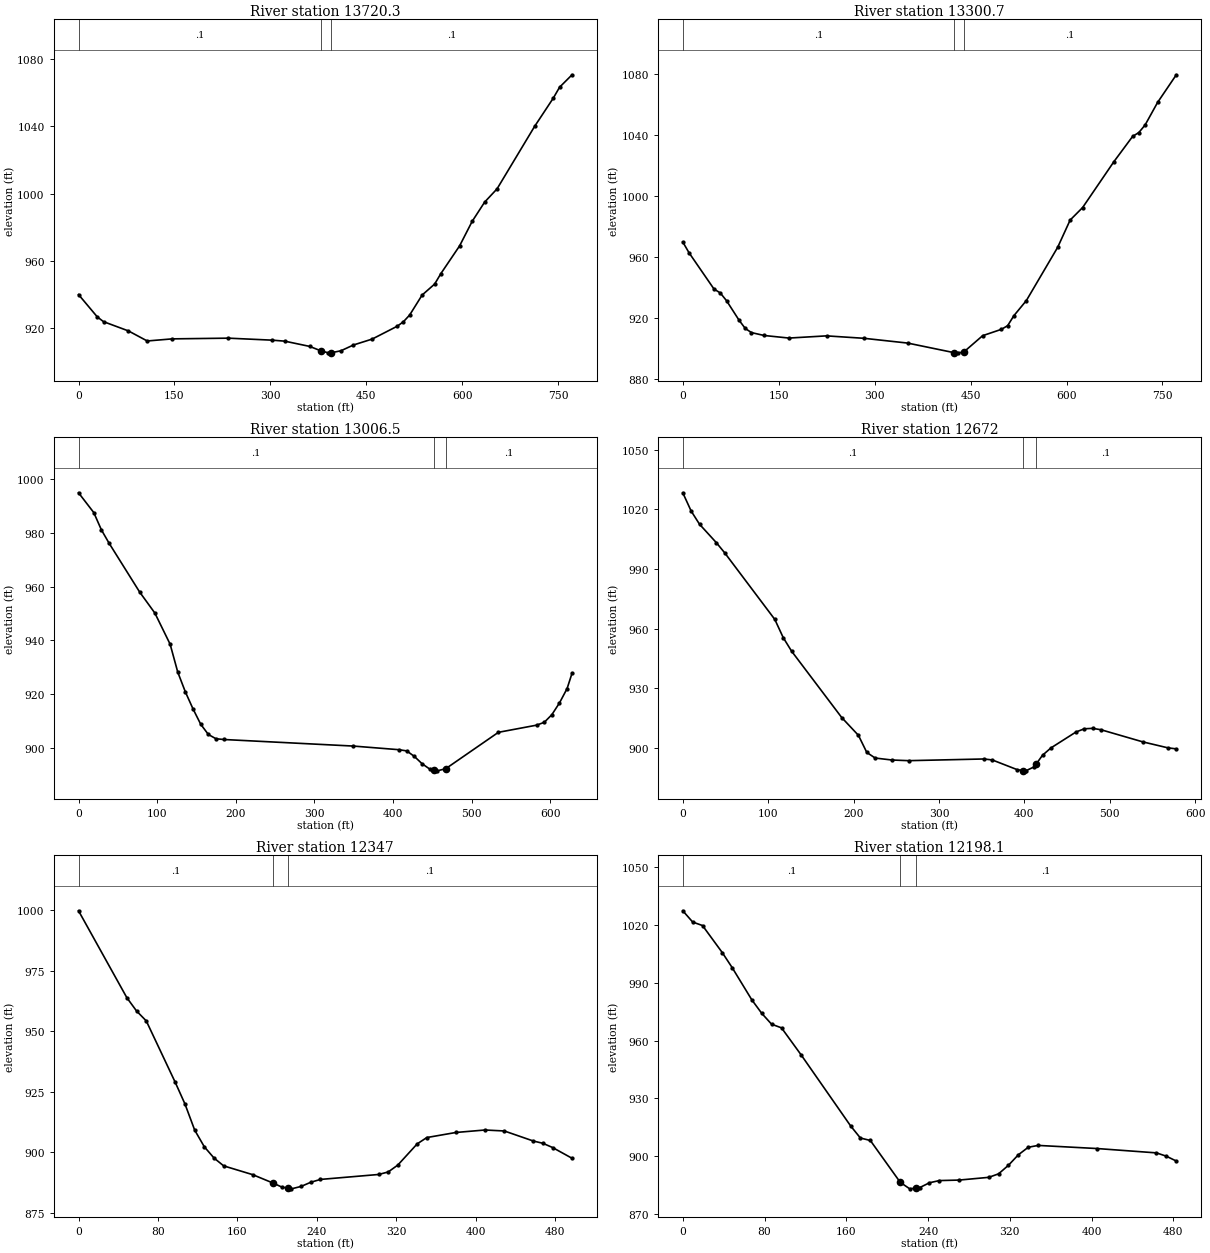
Type RM Length L Ch R = 1 ,13720.3 ,421,419.4,417.8
XS GIS Cut Line= 2
     1734169.995      252042.616       1733679.7      252638.472
#Sta/Elev= 30
       0  940.09    29.3  926.83    39.1  923.98    78.1  918.47   107.4  912.51
   146.5  913.76   234.4  914.18   302.8  912.99   322.3  912.41   361.4  909.28
   379.5  906.57   390.7  905.46   394.5  905.47   410.2  906.68   429.8  910.12
   459.1  913.64   498.2  921.26   507.9  923.92   517.7  927.93   537.2  939.81
   556.8  946.34   566.5  952.55   595.8  969.04   615.4  983.57   634.9  995.01
   654.4 1002.94     713 1039.99   742.3 1056.85   752.1  1063.3   771.6 1070.69
#Mann= 3 , 0 , 0
       0      .1       0   379.5    .045       0   394.5      .1       0
Bank Sta=379.5,394.5
XS Rating Curve= 0 ,0
Exp/Cntr=0.3,0.1

Type RM Length L Ch R = 1 ,13300.7 ,282.1,294.5,306.9
XS GIS Cut Line= 2
     1733817.909      251779.593     1733369.924      252407.879
#Sta/Elev= 30
       0  969.89     9.8   962.8    48.8  938.99    58.6  936.43    68.4  931.33
    87.9  918.56    97.7  913.08   107.4  910.37     127  908.48     166  906.78
   224.7  908.22   283.3  906.62   351.6  903.48   424.1  897.19   429.8  897.07
   439.1  897.54   468.8  908.34   498.2  912.52   507.9  914.92   517.7   921.5
   537.2  931.44   586.1  966.39   605.6  984.29   625.1  992.52     674 1022.65
   703.3 1039.26     713  1041.8   722.8 1046.75   742.3 1061.56   771.6 1079.75
#Mann= 3 , 0 , 0
       0      .1       0   424.1    .045       0   439.1      .1       0
Bank Sta=424.1,439.1
XS Rating Curve= 0 ,0
Exp/Cntr=0.3,0.1

Type RM Length L Ch R = 1 ,13006.5 ,334.1,333.9,333.7
XS GIS Cut Line= 3
     1733831.292      251712.767       1733258.5      251953.702
       1733252.7      251956.141
#Sta/Elev= 30
       0  994.93    19.4  987.55    29.1   981.1    38.8  976.17    77.7  957.96
    97.1  950.11   116.5  938.51   126.2  928.11   135.9  920.72   145.6  914.41
   155.4  908.69   165.1  904.88   174.8  903.29   184.5  903.01   349.5  900.56
   407.8   899.2   417.5  898.75   427.2  896.68   436.9  893.99   446.6  892.01
   452.1  891.62   456.3  891.33   467.1  892.14     534  905.68   582.6  908.35
   592.3   909.4     602  912.25   611.7  916.63   621.4  921.99   627.7  927.72
#Mann= 3 , 0 , 0
       0      .1       0   452.1    .045       0   467.1      .1       0
Bank Sta=452.1,467.1
XS Rating Curve= 0 ,0
Exp/Cntr=0.3,0.1

Type RM Length L Ch R = 1 ,12672   ,334.4,324.9,315.4
XS GIS Cut Line= 2
     1733696.232      251412.984     1733163.427      251637.099
#Sta/Elev= 30
       0 1028.38     9.8 1019.19    19.6 1012.55    39.2 1003.33      49  998.21
   107.8  964.63   117.6  955.52   127.4  948.69   186.1  915.29   205.7  906.32
   215.5  897.72   225.3  894.89   244.9   893.9   264.5  893.57   352.7  894.42
   362.5  893.93   391.9     889   398.6  888.62   401.7  888.45   411.5  890.46
   413.6  891.71   421.3  896.29   431.1  899.96   460.5  907.99   470.2  909.61
     480  909.83   489.8  909.13   538.8  903.02   568.2  900.02     578   899.5
#Mann= 3 , 0 , 0
       0      .1       0   398.6    .045       0   413.6      .1       0
Bank Sta=398.6,413.6
XS Rating Curve= 0 ,0
Exp/Cntr=0.3,0.1

Type RM Length L Ch R = 1 ,12347   ,155.1,148.7,142.4
XS GIS Cut Line= 2
     1733449.583      251131.031     1733114.352      251497.616
#Sta/Elev= 30
       0  999.63    48.7  963.75    58.4  958.32    68.2  954.21    97.4  928.85
   107.1  920.01   116.9  909.22   126.6  902.33   136.4  897.68   146.1  894.45
   175.3  890.83   196.2   887.3   204.6  885.71   211.2  885.21   214.3  884.98
     224  885.97   233.8  887.69   243.5  888.86     302   890.9   311.7  891.93
   321.4  894.78   340.9  903.52   350.6  906.13   379.9  908.22   409.1  909.24
   428.6  908.84   457.8   904.7   467.5  903.75   477.3  901.99   496.8  897.58
#Mann= 3 , 0 , 0
       0      .1       0   196.2    .045       0   211.2      .1       0
Bank Sta=196.2,211.2
XS Rating Curve= 0 ,0
Exp/Cntr=0.3,0.1

Type RM Length L Ch R = 1 ,12198.1 ,183.3,180,176.7
XS GIS Cut Line= 2
     1733289.818       250996.29     1733075.514      251428.985
#Sta/Elev= 30
       0 1027.37     9.7 1021.52    19.3 1019.71    38.6  1005.7    48.3  997.89
    67.6   981.1    77.3  974.12    86.9  968.49    96.6  966.61   115.9   952.5
   164.2  915.73   173.8  909.42   183.5  908.16   212.8  886.42   222.1  883.05
   227.8  883.43   231.8  883.69   241.4  886.21   251.1  887.34   270.4   887.6
   299.4  889.02     309  890.84   318.7   895.3   328.3   900.7     338  904.62
   347.7  905.59   405.6  903.96   463.5  901.71   473.2  899.98   482.9  897.47
#Mann= 3 , 0 , 0
       0      .1       0   212.8    .045       0   227.8      .1       0
Bank Sta=212.8,227.8
XS Rating Curve= 0 ,0
Exp/Cntr=0.3,0.1

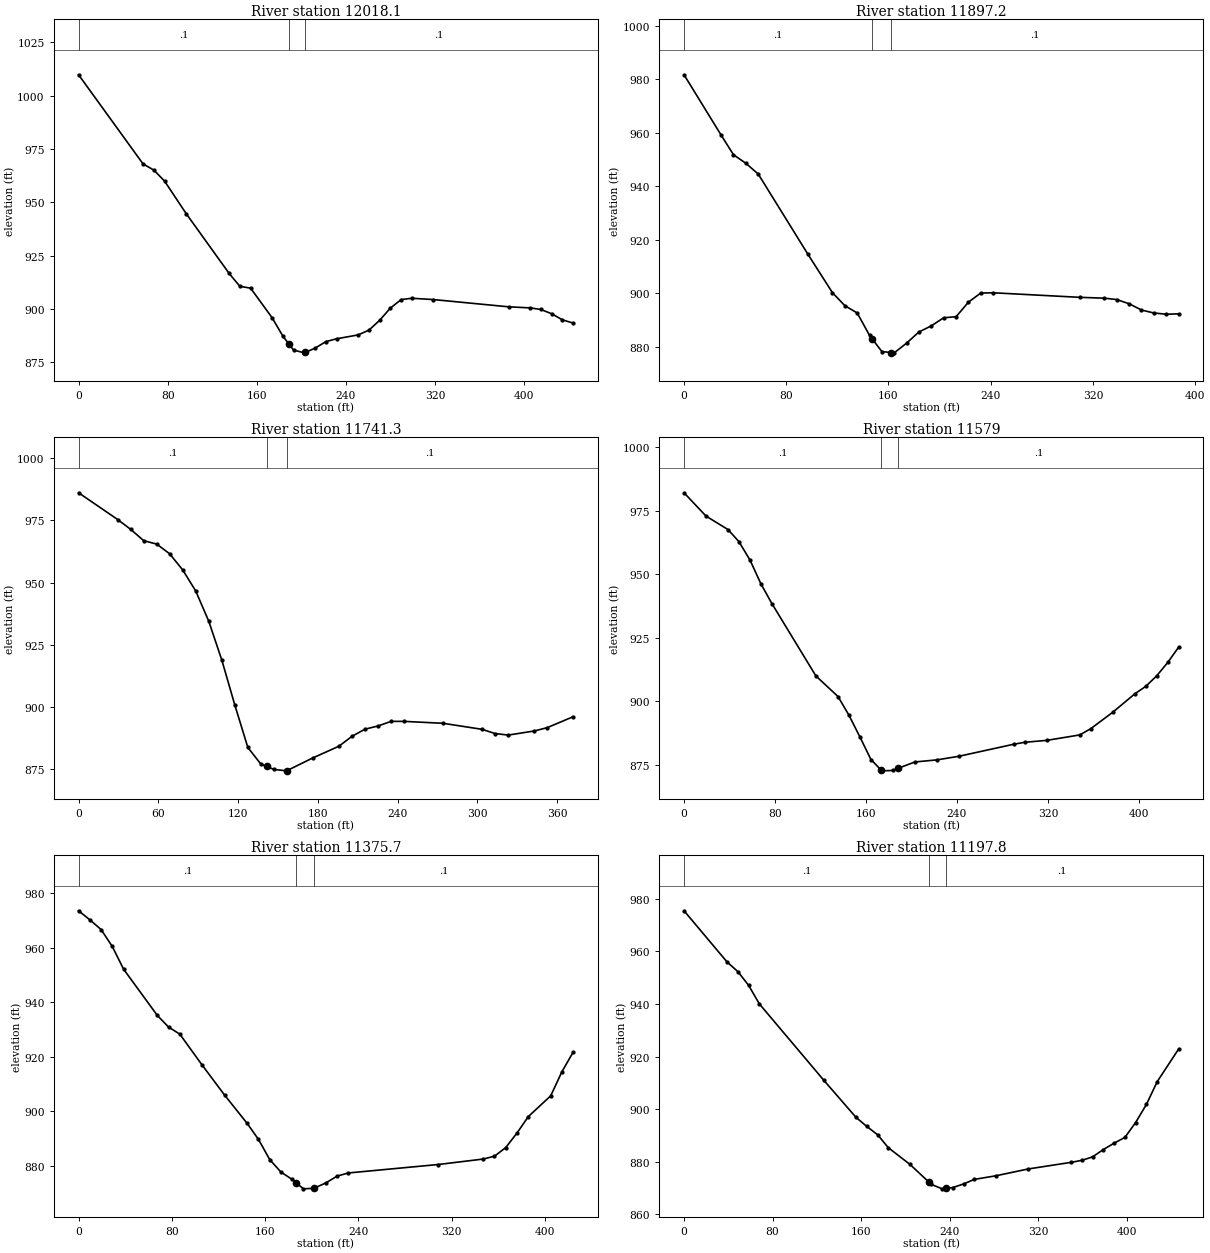
Type RM Length L Ch R = 1 ,12018.1 ,124.2,120.9,117.6
XS GIS Cut Line= 2
     1733092.604      250925.499      1732955.75      251348.063
#Sta/Elev= 30
       0 1009.82    57.9  968.02    67.6  965.13    77.2  959.98    96.6  944.74
   135.2  916.67   144.8  910.64   154.5  909.76   173.8  895.89   183.5  887.24
   188.7  883.71   193.1  880.73   202.8  879.44   203.7  879.65   212.4  881.64
   222.1   884.7   231.7  886.03     251  887.84   260.7  890.05   270.4   894.7
     280  900.43   289.7  904.41   299.3  905.03   318.6  904.42   386.2  901.02
   405.6  900.51   415.2  899.77   424.9  897.76   434.5  894.91   444.2  893.39
#Mann= 3 , 0 , 0
       0      .1       0   188.7    .045       0   203.7      .1       0
Bank Sta=188.7,203.7
XS Rating Curve= 0 ,0
Exp/Cntr=0.3,0.1

Type RM Length L Ch R = 1 ,11897.2 ,156.2,155.9,155.5
XS GIS Cut Line= 2
     1732940.132      250931.364      1732876.44       251313.15
#Sta/Elev= 30
       0  981.69      29  959.17    38.7  951.81    48.4  948.62    58.1  944.57
    96.8  914.74   116.1  900.31   125.8  895.44   135.5   892.7   145.2   884.3
   147.1  883.11   154.8  878.28   162.1  877.92   164.5   877.8   174.2  881.44
   183.8  885.59   193.5  887.88   203.2   890.9   212.9   891.3   222.6  896.75
   232.2  900.14   241.9  900.24   309.6  898.54     329  898.22   338.7   897.7
   348.4  896.12     358   893.8   367.7  892.69   377.4  892.23   387.1  892.36
#Mann= 3 , 0 , 0
       0      .1       0   147.1    .045       0   162.1      .1       0
Bank Sta=147.1,162.1
XS Rating Curve= 0 ,0
Exp/Cntr=0.3,0.1

Type RM Length L Ch R = 1 ,11741.3 ,151.9,162.3,172.8
XS GIS Cut Line= 2
     1732782.992      250912.493     1732727.494      251280.382
#Sta/Elev= 30
       0  986.04    29.4  975.31    39.2  971.36      49  966.81    58.8  965.44
    68.5  961.55    78.3  955.09    88.1  946.63    97.9   934.5   107.7  918.94
   117.5  900.87   127.3  883.84   137.1  877.16   141.4  876.23   146.9  875.03
   156.4  874.46   176.2  879.65   195.8  884.33   205.6  888.31   215.4  891.18
   225.2  892.46     235  894.31   244.8  894.31   274.1  893.54   303.5  891.11
   313.3  889.41   323.1  888.81   342.7  890.45   352.5   891.8     372  896.19
#Mann= 3 , 0 , 0
       0      .1       0   141.4    .045       0   156.4      .1       0
Bank Sta=141.4,156.4
XS Rating Curve= 0 ,0
Exp/Cntr=0.3,0.1

Type RM Length L Ch R = 1 ,11579   ,199.7,203.3,206.9
XS GIS Cut Line= 2
     1732710.241      250865.857     1732459.592      251221.444
#Sta/Elev= 30
       0  982.12    19.3  972.96    38.7  967.63    48.3  962.88      58  955.65
    67.7   946.2    77.3  938.49     116  910.03   135.4  901.95     145  894.62
   154.7  886.02   164.4  877.13   173.5  872.94     174  872.71   183.7  872.85
   188.5  873.74     203   876.2   222.4  877.02   241.7  878.44     290  883.18
   299.7  883.95     319   884.7     348  886.84   357.7   889.3     377  895.75
   396.4     903     406  905.93   415.7   910.1   425.4  915.36     435  921.39
#Mann= 3 , 0 , 0
       0      .1       0   173.5    .045       0   188.5      .1       0
Bank Sta=173.5,188.5
XS Rating Curve= 0 ,0
Exp/Cntr=0.3,0.1

Type RM Length L Ch R = 1 ,11375.7 ,176.2,177.8,179.4
XS GIS Cut Line= 2
     1732587.647      250744.446     1732291.557       251048.09
#Sta/Elev= 30
       0  973.46     9.6  970.16    19.3  966.59    28.9  960.37    38.6  952.04
    67.5  935.11    77.1  930.86    86.8  928.24     106  916.87   125.3  905.84
   144.6   895.5   154.2  889.68   163.9  882.25   173.5  877.69   183.1     875
   186.8  873.68   192.8  871.54   201.8  871.75   212.1  873.73   221.7  876.22
   231.3  877.36   308.4  880.46     347  882.46   356.6  883.51   366.3  886.68
   375.9     892   385.6  898.02   404.8  905.63   414.5  914.53   424.1  921.68
#Mann= 3 , 0 , 0
       0      .1       0   186.8    .045       0   201.8      .1       0
Bank Sta=186.8,201.8
XS Rating Curve= 0 ,0
Exp/Cntr=0.3,0.1

Type RM Length L Ch R = 1 ,11197.8 ,236.3,240.9,245.6
XS GIS Cut Line= 2
     1732502.225      250601.263     1732168.081      250898.044
#Sta/Elev= 30
       0  975.48    38.9  955.98    48.6  952.34    58.3  947.13      68  940.07
   126.3  910.96   155.4  896.84   165.2  893.38   174.9  890.23   184.6  885.29
     204  878.99   221.5  872.12   223.5  871.34   233.2  869.65   236.5  869.82
   242.9  870.14   252.6  871.52   262.3  873.25   281.8  874.62   310.9  877.21
   349.8  879.74   359.5   880.5   369.2  881.84   378.9  884.62   388.6  887.04
   398.3  889.22     408  894.88   417.8  901.81   427.5  910.44   446.9  922.88
#Mann= 3 , 0 , 0
       0      .1       0   221.5    .045       0   236.5      .1       0
Bank Sta=221.5,236.5
XS Rating Curve= 0 ,0
Exp/Cntr=0.3,0.1

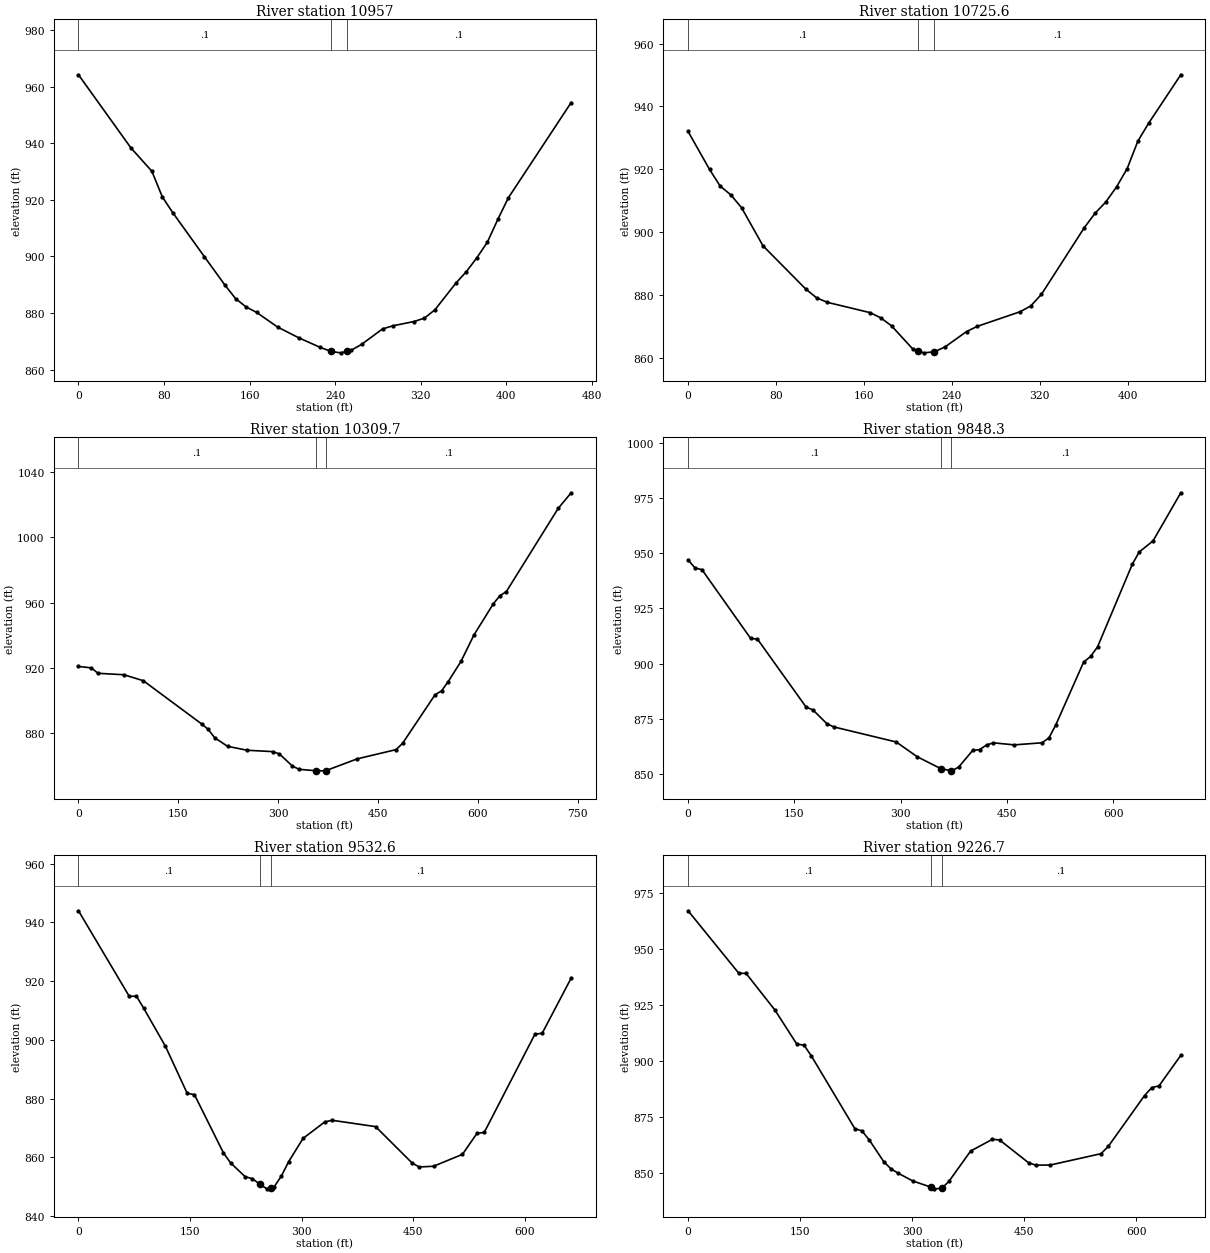
Type RM Length L Ch R = 1 ,10957   ,235.1,231.2,227.2
XS GIS Cut Line= 2
     1732404.232      250437.008     1732004.529      250666.105
#Sta/Elev= 30
       0   964.2      49  938.37    68.6  930.12    78.4  921.03    88.2  915.44
   117.6  899.97   137.2  889.73     147  885.04   156.8  882.13   166.6   880.2
   186.2  875.03   205.8  871.27   225.4  867.95   236.2   866.4   245.1  865.92
   251.2  866.48   254.9  866.82   264.7  868.91   284.3  874.37   294.1  875.49
   313.7  876.98   323.5   878.2   333.3  881.13   352.9  890.57   362.7  894.63
   372.5  899.52   382.3  905.02   392.1  913.08   401.9  920.68   460.7   954.4
#Mann= 3 , 0 , 0
       0      .1       0   236.2    .045       0   251.2      .1       0
Bank Sta=236.2,251.2
XS Rating Curve= 0 ,0
Exp/Cntr=0.3,0.1

Type RM Length L Ch R = 1 ,10725.6 ,418.5,416.1,413.6
XS GIS Cut Line= 2
     1732267.556      250207.911     1731922.252       250494.07
#Sta/Elev= 30
       0  932.04    19.5  919.97    29.2  914.66      39  911.83    48.8   907.7
    68.2  895.63   107.2  881.84     117  879.06   126.7  877.64   165.7  874.35
   175.5  872.67   185.2  870.15   204.7   862.7   209.3  862.16   214.5  861.55
   224.3  861.88     234  863.46   253.5  868.33   263.2  869.98   302.2  874.63
     312   876.5   321.7   880.2   360.7  901.42   370.5  906.02   380.2  909.56
     390  914.38   399.7  920.22   409.5  929.02   419.2  934.65   448.5   950.1
#Mann= 3 , 0 , 0
       0      .1       0   209.3    .045       0   224.3      .1       0
Bank Sta=209.3,224.3
XS Rating Curve= 0 ,0
Exp/Cntr=0.3,0.1

Type RM Length L Ch R = 1 ,10309.7 ,473.9,461.3,448.6
XS GIS Cut Line= 2
     1732134.223      249730.418      1731624.23      250267.032
#Sta/Elev= 30
       0  920.97    19.5   920.1    29.2  916.78    68.2   915.9    97.4  912.25
   185.1  885.78   194.8   882.5   204.6  877.37     224  872.11   253.3  869.71
   292.2  868.86     302  867.41   321.4  860.05   331.2  858.06   356.8  857.16
   370.2  857.11   371.8  857.25   418.8  864.44   477.3   870.1     487  873.96
   535.7  903.62   545.5  906.03   555.2   911.5   574.7  924.05   594.2  940.23
   623.4  959.36   633.2  964.22   642.9  966.78   720.8  1017.7   740.3 1027.22
#Mann= 3 , 0 , 0
       0      .1       0   356.8    .045       0   371.8      .1       0
Bank Sta=356.8,371.8
XS Rating Curve= 0 ,0
Exp/Cntr=0.3,0.1

Type RM Length L Ch R = 1 ,9848.3  ,317.2,315.6,314
XS GIS Cut Line= 2
     1731536.231      249459.755     1731392.019      250139.543
#Sta/Elev= 30
       0  946.93     9.8  943.31    19.6  942.52    88.1  911.43    97.9  911.04
   166.4  880.28   176.2  878.94   195.8  872.72   205.5  871.28   293.6  864.44
     323  857.79   356.3  852.39   371.3  851.38   371.9  851.37   381.7  853.08
   401.3  860.59   411.1  860.97   420.9  863.08   430.6  864.06     460  863.14
   499.2  864.08     509  866.29   518.7  872.25   557.9  900.66   567.7  903.19
   577.5  907.53   626.4  944.89   636.2  950.52   655.8  955.58   694.9  977.37
#Mann= 3 , 0 , 0
       0      .1       0   356.3    .045       0   371.3      .1       0
Bank Sta=356.3,371.3
XS Rating Curve= 0 ,0
Exp/Cntr=0.3,0.1

Type RM Length L Ch R = 1 ,9532.6  ,308.5,305.8,303.2
XS GIS Cut Line= 2
     1731198.933      249459.755     1731107.957       250115.68
#Sta/Elev= 30
       0  943.92    68.2  914.82    77.9  914.86    87.6  910.78   116.9  897.79
   146.1  881.81   155.8  881.38   194.8  861.55   204.5  858.12     224  853.44
   233.7  852.77   243.8  850.87   253.2  849.31   258.8  849.69   262.9  849.96
   272.7  853.67   282.4  858.54   301.9  866.48   331.1   872.1   340.8  872.64
   399.3  870.48     448  858.21   457.7  856.75   477.2  856.99   516.1  861.05
   535.6   868.2   545.3  868.48   613.5  901.95   623.2  902.23   662.2  921.03
#Mann= 3 , 0 , 0
       0      .1       0   243.8    .045       0   258.8      .1       0
#XS Ineff= 2 , 0
                          339.77          872.44
Permanent Ineff=
       F       F
Bank Sta=243.8,258.8
XS Rating Curve= 0 ,0
Exp/Cntr=0.3,0.1

Type RM Length L Ch R = 1 ,9226.7  ,397.5,399,400.5
XS GIS Cut Line= 2
     1730872.671      249439.442     1730859.915      250098.832
#Sta/Elev= 30
       0   967.2    67.9  939.25    77.6   939.2   116.4  922.72   145.5  907.57
   155.2   907.1   164.9  902.32   223.1  869.81   232.8  868.71   242.5  864.71
   261.9  854.99   271.6  851.76   281.3  849.81   300.7  846.36   324.5  843.65
   329.8  842.83   339.5  843.06   349.2  846.18   378.2  859.73   407.4     865
     417  864.68   455.8  854.48   465.5  853.42   484.9  853.49   552.8  858.56
   562.5  861.84     611  884.55   620.7  888.12   630.4  888.89   659.5  902.52
#Mann= 3 , 0 , 0
       0      .1       0   324.5    .045       0   339.5      .1       0
Bank Sta=324.5,339.5
XS Rating Curve= 0 ,0
Exp/Cntr=0.3,0.1

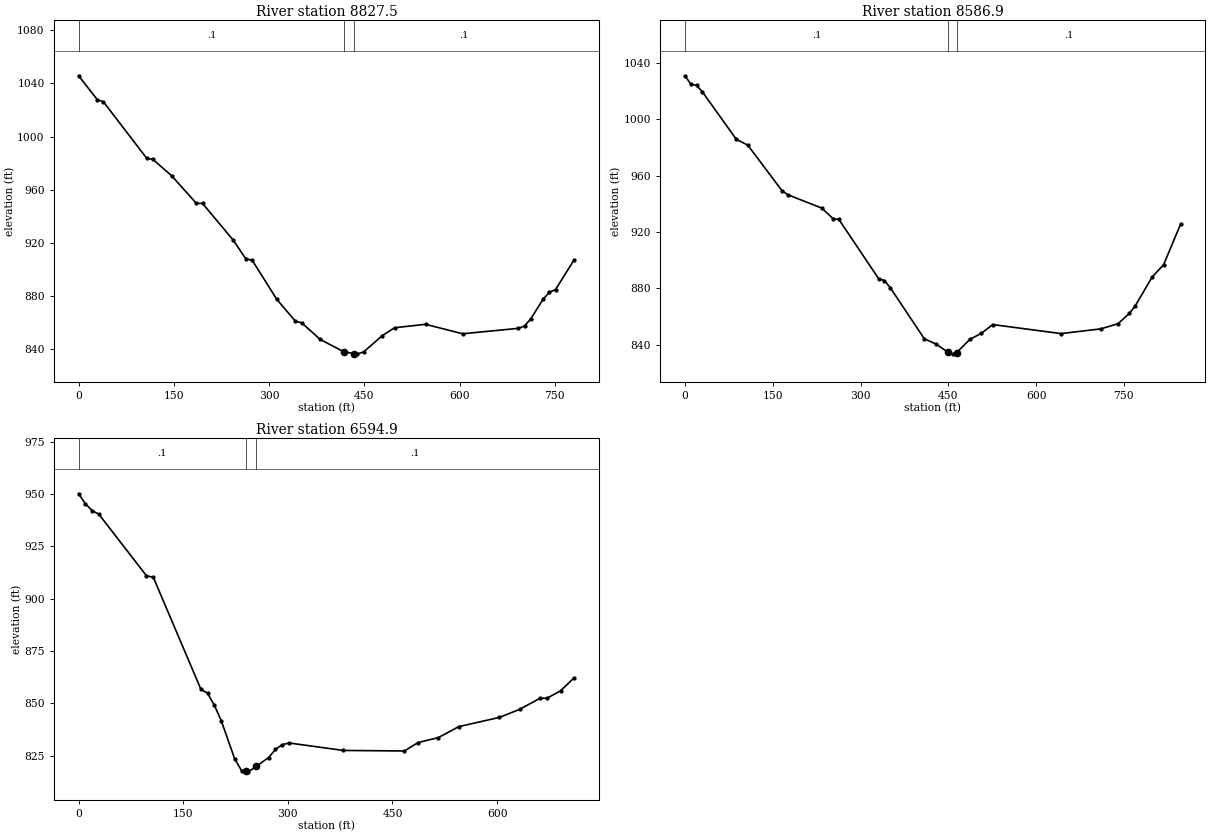
Type RM Length L Ch R = 1 ,8827.5  ,238.4,240.7,243.1
XS GIS Cut Line= 2
     1730509.959      249293.138     1730441.098      250070.384
#Sta/Elev= 30
       0 1045.82    29.3 1027.86      39 1026.23   107.3  983.49     117  982.73
   146.3  970.46   185.3  949.65   195.1  949.51   243.8  921.61   263.4  907.58
   273.1  906.81   312.1  877.09   341.4  860.62   351.1  859.49   380.4   846.9
   418.1  837.45   433.1  836.29   438.9  836.04   448.7  837.45   477.9  849.68
   497.4  855.72   546.2  858.32   604.7  851.18   692.5  855.28   702.3  857.07
     712   862.5   731.5  877.34   741.3  882.48     751  884.56   780.3  907.02
#Mann= 3 , 0 , 0
       0      .1       0   418.1    .045       0   433.1      .1       0
Bank Sta=418.1,433.1
XS Rating Curve= 0 ,0
Exp/Cntr=0.3,0.1

Type RM Length L Ch R = 1 ,8586.9  ,1992,1991.7,1991.4
XS GIS Cut Line= 2
     1730323.737      249219.887      1730162.62      250051.468
#Sta/Elev= 30
       0 1031.02     9.7 1025.07    19.5  1024.2    29.2 1019.79    87.6  985.86
   107.1  981.78   165.5  949.45   175.2  946.54   233.7     937   253.1  929.41
   262.9  928.95     331  886.74   340.8  885.56   350.5  880.55   408.9  844.14
   428.4  840.54     449   834.7   457.6  833.46     464  834.28   486.8  843.78
   506.3  848.01   525.8  854.25   642.6  847.85   710.7  851.21     740  854.88
   759.4  862.21   769.2  867.42   798.4   888.1   817.8  896.72     847   925.7
#Mann= 3 , 0 , 0
       0      .1       0     449    .045       0     464      .1       0
Bank Sta=449,464
XS Rating Curve= 0 ,0
Exp/Cntr=0.3,0.1

Type RM Length L Ch R = 1 ,6594.9  ,189.4,192.2,195
XS GIS Cut Line= 2
      1728359.52      249009.177     1728206.702      249703.026
#Sta/Elev= 30
       0  950.06     9.7  945.27    19.5  942.03    29.2  940.23    97.3  910.93
   107.1  910.21   175.2  856.85   184.9  854.82   194.6  849.14   204.4  841.84
   223.8  823.53   233.6  817.96   239.6   817.6   243.3  817.38   254.6  819.98
   272.5  824.21   282.2  828.11     292  830.34   301.7  831.15   379.6  827.59
   467.2  827.34   486.6  831.34   515.8  833.73     545  838.95   603.4  843.36
   632.6  847.24   661.8  852.52   671.6  852.51     691  856.06   710.5  862.26
#Mann= 3 , 0 , 0
       0      .1       0   239.6    .045       0   254.6      .1       0
#XS Ineff= 2 , 0
                          301.86          830.86
Permanent Ineff=
       F       F
Bank Sta=239.6,254.6
XS Rating Curve= 0 ,0
Exp/Cntr=0.3,0.1