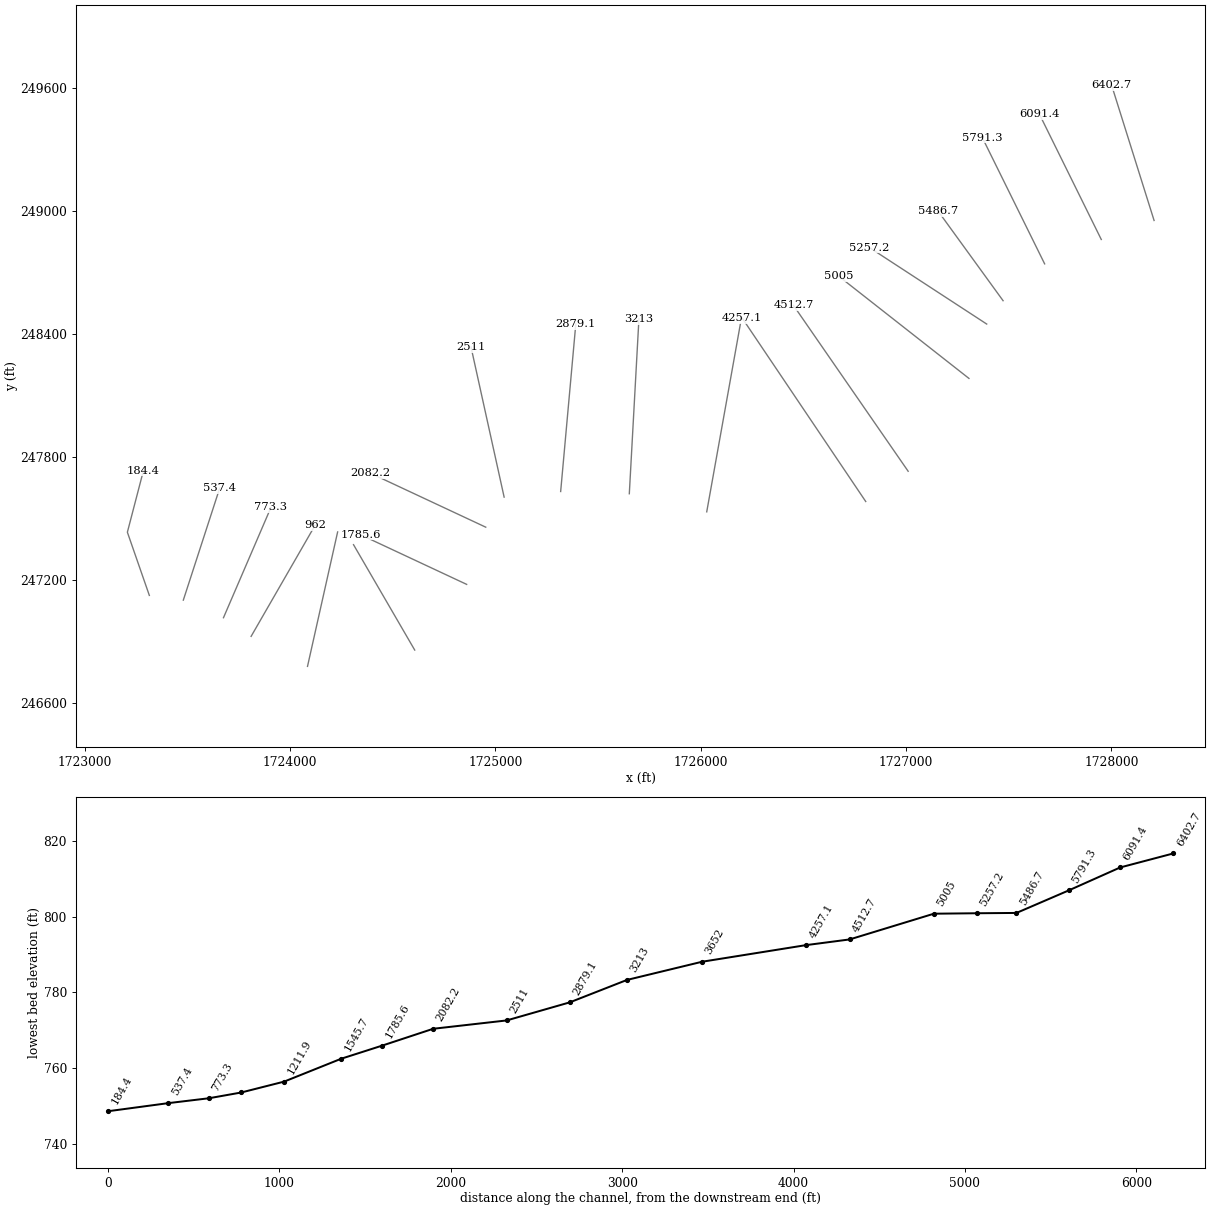
HEC-RAS study ELKCRK.prj: ELKCRK

--- ELKCRK.g01 (geometry) --- (continued)

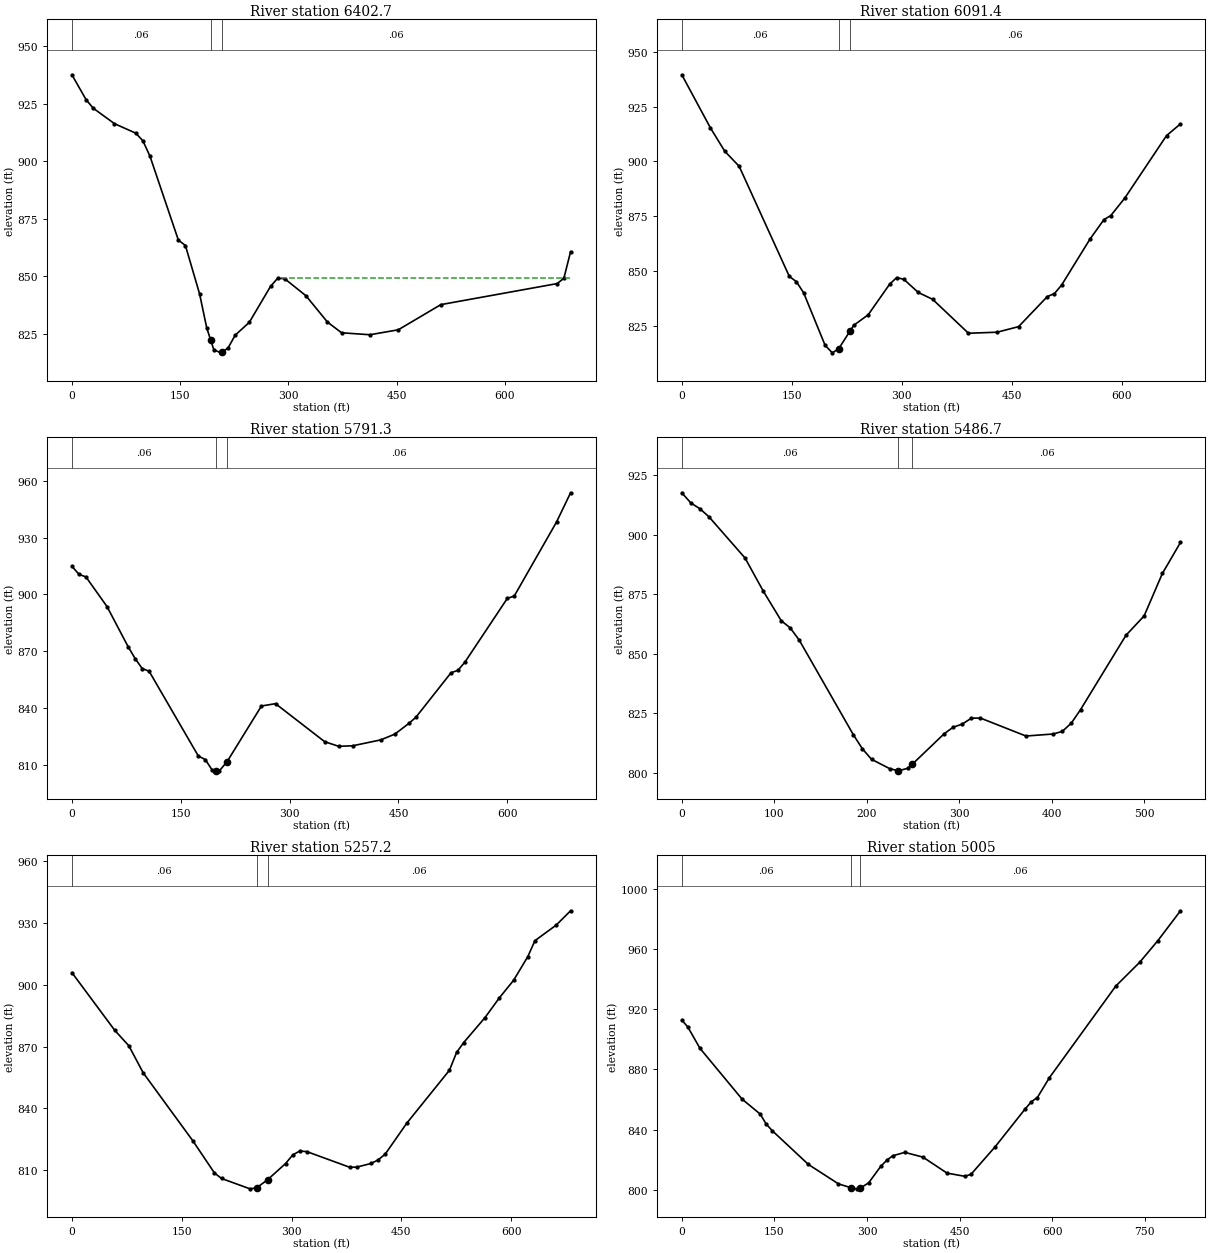
Type RM Length L Ch R = 1 ,6402.7  ,307.9,311.3,314.8
XS GIS Cut Line= 3
     1728207.797      248954.487     1728037.278       249498.72
     1728001.158      249614.003
#Sta/Elev= 30
       0  937.57    19.7  926.71    29.5  923.05      59   916.3    88.5  912.18
    98.3  908.89   108.2  902.14   147.5  865.69   157.3  863.31     177  842.21
   186.8  827.53   192.4  822.11   196.7  817.95   206.5  816.63   207.4  816.82
   216.3  818.68   226.2  824.28   245.8  829.88   275.3  845.54   285.2  849.09
     295  848.84   324.5  841.41     354  830.07   373.7  825.35     413   824.5
   452.3  826.65   511.3   837.6   672.5  846.75   681.8  849.05   691.1  860.62
#Mann= 3 , 0 , 0
       0     .06       0   192.4    .045       0   207.4     .06       0
#XS Ineff= 2 , 0
                          289.55          849.39
Permanent Ineff=
       F       F
Bank Sta=192.4,207.4
XS Rating Curve= 0 ,0
Exp/Cntr=0.3,0.1

Type RM Length L Ch R = 1 ,6091.4  ,300.1,300.1,300.1
XS GIS Cut Line= 3
     1727950.615      248861.781     1727713.009      249344.061
     1727649.979      249471.996
#Sta/Elev= 30
       0  939.45    39.1  915.24    58.6  904.64    78.2  897.82   146.6  847.73
   156.4  845.26   166.2  840.21   195.5  816.31   205.3  812.92   214.1  814.84
   229.1  822.66   234.6  825.47   254.2  830.23   283.5  844.16   293.2   847.2
     303  846.33   322.6  840.38   342.1  837.28     391  821.83   430.1  822.31
   459.4  824.85   498.5  838.51   508.3   839.9   518.1  843.78   556.6  864.59
   575.7  873.52   585.2  875.41   604.2  883.32   661.2  911.78   680.2   917.1
#Mann= 3 , 0 , 0
       0     .06       0   214.1    .045       0   229.1     .06       0
#XS Ineff= 2 , 0
                          293.89           846.9
Permanent Ineff=
       F       F
Bank Sta=214.1,229.1
XS Rating Curve= 0 ,0
Exp/Cntr=0.3,0.1

Type RM Length L Ch R = 1 ,5791.3  ,300.8,304.6,308.4
XS GIS Cut Line= 3
     1727674.787      248742.827     1727443.897      249211.476
     1727371.104      249359.227
#Sta/Elev= 30
       0  914.87     9.7  910.62    19.4  909.22    48.4  893.57    77.4  872.45
    87.1  866.15    96.8  860.89   106.4  859.44   174.2   814.7   183.8  812.82
   193.5  807.18   198.9  807.01   203.2  806.87   213.9  811.76   261.2   841.1
   280.6  842.33   348.3  822.26   367.6  819.82     387   820.1   425.7  823.22
     445  826.25   464.4  831.92   474.1  835.19   522.4  858.63   532.1  859.96
   541.8  864.38     600  897.89   609.6  899.17   667.8   938.2   687.2  953.66
#Mann= 3 , 0 , 0
       0     .06       0   198.9    .045       0   213.9     .06       0
Bank Sta=198.9,213.9
XS Rating Curve= 0 ,0
Exp/Cntr=0.3,0.1

Type RM Length L Ch R = 1 ,5486.7  ,221.2,229.4,237.7
XS GIS Cut Line= 3
     1727472.434      248562.957      1727334.91      248752.896
      1727156.13      248999.814
#Sta/Elev= 30
       0  917.55     9.8  913.27    19.5  910.88    29.3   907.5    68.4  890.18
    87.9  876.44   107.5  863.91   117.2   860.9     127  855.76   185.6  816.02
   195.4  810.11   205.2  805.77   224.7  801.88   234.3  800.94   244.3  802.02
   249.3  803.72   283.7  816.48   293.5  819.25   303.3  820.54   313.2  823.04
     323  823.06   372.2  815.54   401.7  816.39   411.5  817.48   421.3  820.98
   431.2  826.59   480.3  857.76     500  865.92   519.7   883.7   539.3  896.71
#Mann= 3 , 0 , 0
       0     .06       0   234.3    .045       0   249.3     .06       0
Bank Sta=234.3,249.3
XS Rating Curve= 0 ,0
Exp/Cntr=0.3,0.1

Type RM Length L Ch R = 1 ,5257.2  ,254.6,252.4,250.3
XS GIS Cut Line= 2
     1727392.636      248449.076     1726822.624      248821.628
#Sta/Elev= 30
       0  905.97    58.4  877.96    77.8  870.38    97.3  857.28   165.4  824.08
   194.6   808.6   204.3   805.9   243.2  800.86   252.3  801.35   267.3  805.31
   291.8  813.16   301.6  817.37   311.3  819.27     321  818.93   379.4  811.34
   389.1  811.43   408.6   813.2   418.3  814.94     428   817.8   457.2  832.73
   515.6  858.52   525.3  867.14     535  871.95   564.2  884.13   583.7  893.67
   603.1  902.18   622.6  913.74   632.3  921.48   661.5   929.1     681  936.02
#Mann= 3 , 0 , 0
       0     .06       0   252.3    .045       0   267.3     .06       0
#XS Ineff= 2 , 0
                          318.83          818.32
Permanent Ineff=
       F       F
Bank Sta=252.3,267.3
XS Rating Curve= 0 ,0
Exp/Cntr=0.3,0.1

Type RM Length L Ch R = 1 ,5005    ,498.1,491.6,485.1
XS GIS Cut Line= 3
      1727306.22      248183.725      1726699.77      248660.775
     1726671.075      248683.347
#Sta/Elev= 30
       0  912.73     9.8  908.12    29.3  894.06    97.7  860.26     127  850.38
   136.7  843.77   146.5  839.34   205.1  816.94   253.9  804.02   273.8  801.52
   283.2  800.74   288.8  801.13   302.8  804.72   322.3  815.62   332.1  819.72
   341.8  822.69   361.4  824.94   390.7   821.8   429.8  811.17     459  809.03
   468.8  810.46   507.9  828.73   556.7  853.92   566.5  858.55   576.2  861.36
   595.8  874.57   703.2  935.29   742.3  951.23   771.6  965.56   808.1  985.29
#Mann= 3 , 0 , 0
       0     .06       0   273.8    .045       0   288.8     .06       0
Bank Sta=273.8,288.8
XS Rating Curve= 0 ,0
Exp/Cntr=0.3,0.1

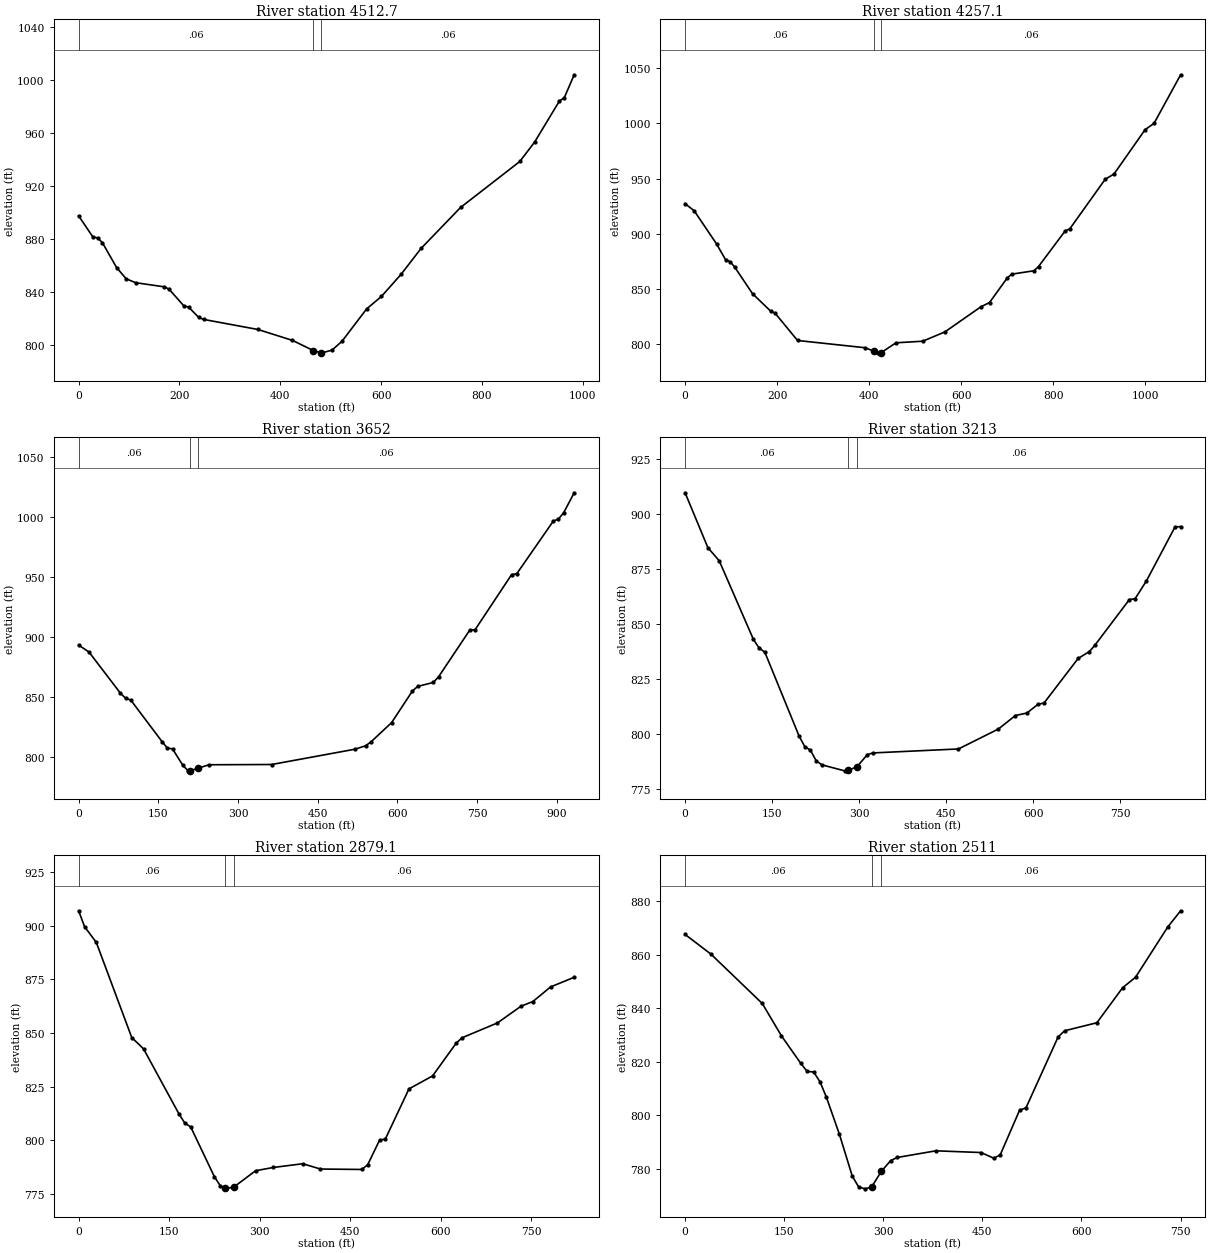
Type RM Length L Ch R = 1 ,4512.7  ,256,255.8,255.6
XS GIS Cut Line= 3
     1727010.067      247730.723     1726908.319      247878.194
     1726451.871       248539.76
#Sta/Elev= 30
       0  897.48    28.3  881.53    37.7  880.83    47.2   877.2    75.4  858.36
    94.3   849.9   113.2  846.96   169.7  843.86   179.2  842.13   208.6  829.48
   218.4  828.39     238  820.81   247.8  819.22   355.6  811.61   424.2  803.37
   465.4  795.69   480.4  794.04     483  793.96   502.6  796.04   522.2   802.6
   571.2  827.16   600.6  836.57   639.8  853.39   679.1  872.82   757.5   903.8
   875.1  938.58   904.5  953.28   953.5  984.18   963.3  986.78   982.9  1004.1
#Mann= 3 , 0 , 0
       0     .06       0   465.4    .045       0   480.4     .06       0
Bank Sta=465.4,480.4
XS Rating Curve= 0 ,0
Exp/Cntr=0.3,0.1

Type RM Length L Ch R = 1 ,4257.1  ,622.2,605,587.7
XS GIS Cut Line= 4
     1726803.431      247583.126      1726601.65      247883.324
     1726347.826      248260.946     1726202.525      248477.117
#Sta/Elev= 30
       0  927.26    19.6  920.98    68.4  890.93      88  876.62    97.8  874.88
   107.5  870.17   146.6  845.92   185.7  830.25   195.5  828.36   244.4  803.62
   390.8  797.09   411.3  793.86   419.8  792.45   426.3  792.69   458.5  801.53
   516.6  802.96     565  811.43   642.4  833.92   661.8  837.94   700.5   860.3
   710.2  863.59   758.6  866.66   768.3   870.5   826.4  902.79     836  904.42
   913.2  949.38   932.5  954.19    1000  994.27  1019.3  999.85  1077.2 1043.84
#Mann= 3 , 0 , 0
       0     .06       0   411.3    .045       0   426.3     .06       0
Bank Sta=411.3,426.3
XS Rating Curve= 0 ,0
Exp/Cntr=0.3,0.1

Type RM Length L Ch R = 1 ,3652    ,436.3,438.7,441.2
XS GIS Cut Line= 2
      1726029.11      247532.626     1726193.192       248450.63
#Sta/Elev= 30
       0  893.25    19.6  887.32    78.5  853.07    88.4  848.73    98.2  847.22
   157.1  812.43   166.9  807.17   176.7  806.42   196.3  792.56   206.1  788.08
   209.6  788.14   224.6  790.26   245.4  793.16   363.2  793.37   520.3  806.18
   539.9  808.99   549.7  812.08     589  828.37   628.2  854.81   638.1  858.65
   667.5  861.94   677.3  866.63   736.2  905.77     746  905.95   814.8  952.06
   824.6  952.87   893.3  996.81   903.1  998.54   912.9 1003.88   932.6  1020.5
#Mann= 3 , 0 , 0
       0     .06       0   209.6    .045       0   224.6     .06       0
Bank Sta=209.6,224.6
XS Rating Curve= 0 ,0
Exp/Cntr=0.3,0.1

Type RM Length L Ch R = 1 ,3213    ,334.4,333.8,333.1
XS GIS Cut Line= 2
     1725652.067      247620.995     1725698.894      248473.841
#Sta/Elev= 30
       0  909.57    39.3  884.63    58.9  878.66   117.8  842.94   127.6  839.06
   137.4  837.18   196.4  799.12   206.2   794.3     216  792.66   225.8  787.91
   235.6  786.02   274.9  783.28   281.1  783.56   296.1  785.08   314.2  790.67
     324  791.42   471.2  793.22     540  802.28   569.4  808.41   589.1  809.53
   608.7  813.58   618.5  814.03   677.4  834.32     697  837.48   706.9  840.54
   765.8  861.09   775.6  861.45   795.2  869.58   844.3     894   854.1  894.23
#Mann= 3 , 0 , 0
       0     .06       0   281.1    .045       0   296.1     .06       0
Bank Sta=281.1,296.1
XS Rating Curve= 0 ,0
Exp/Cntr=0.3,0.1

Type RM Length L Ch R = 1 ,2879.1  ,361.3,368.1,374.8
XS GIS Cut Line= 2
     1725317.739      247631.858     1725391.521      248449.541
#Sta/Elev= 30
       0  906.98     9.8  899.59    29.3  892.21      88   847.9   107.5  842.64
   166.2  812.31   175.9  808.02   185.7  806.23   224.8  783.08   234.6  778.83
     243  777.58   244.4  777.37     258  778.39   293.2  785.81   322.5  787.33
   371.4  789.07   400.7   786.6   469.2   786.4   478.9  788.61   498.5  800.01
   508.2  800.61   547.3  823.96   586.4     830   625.5  845.28   635.3  847.79
   693.9   854.7     733  862.51   752.6  864.68   781.9  871.48     821  875.98
#Mann= 3 , 0 , 0
       0     .06       0     243    .045       0     258     .06       0
#XS Ineff= 2 , 0
                          370.24          788.83
Permanent Ineff=
       F       F
Bank Sta=243,258
XS Rating Curve= 0 ,0
Exp/Cntr=0.3,0.1

Type RM Length L Ch R = 1 ,2511    ,408.2,428.8,449.5
XS GIS Cut Line= 3
     1725042.449      247604.493     1724971.299      247927.539
     1724881.118      248336.993
#Sta/Elev= 30
       0  867.54    38.9  860.25   116.8  841.79   145.9  829.68   175.1  819.44
   184.8  816.41   194.6  816.24   204.3  812.52     214  806.72   233.5  793.03
     253   777.4   262.7  773.31   272.4  772.61   282.2  773.27   297.2   779.2
   311.3  783.17   321.1  784.31   379.5   786.8   447.8  786.16   467.3  784.05
     477  785.28   506.3  801.94     516  802.84   564.8  829.38   574.6  831.61
   623.3  834.59   662.3  847.67   681.8  851.56   730.6  870.33   750.1  876.38
#Mann= 3 , 0 , 0
       0     .06       0   282.2    .045       0   297.2     .06       0
#XS Ineff= 2 , 0
                           379.1           786.5
Permanent Ineff=
       F       F
Bank Sta=282.2,297.2
XS Rating Curve= 0 ,0
Exp/Cntr=0.3,0.1

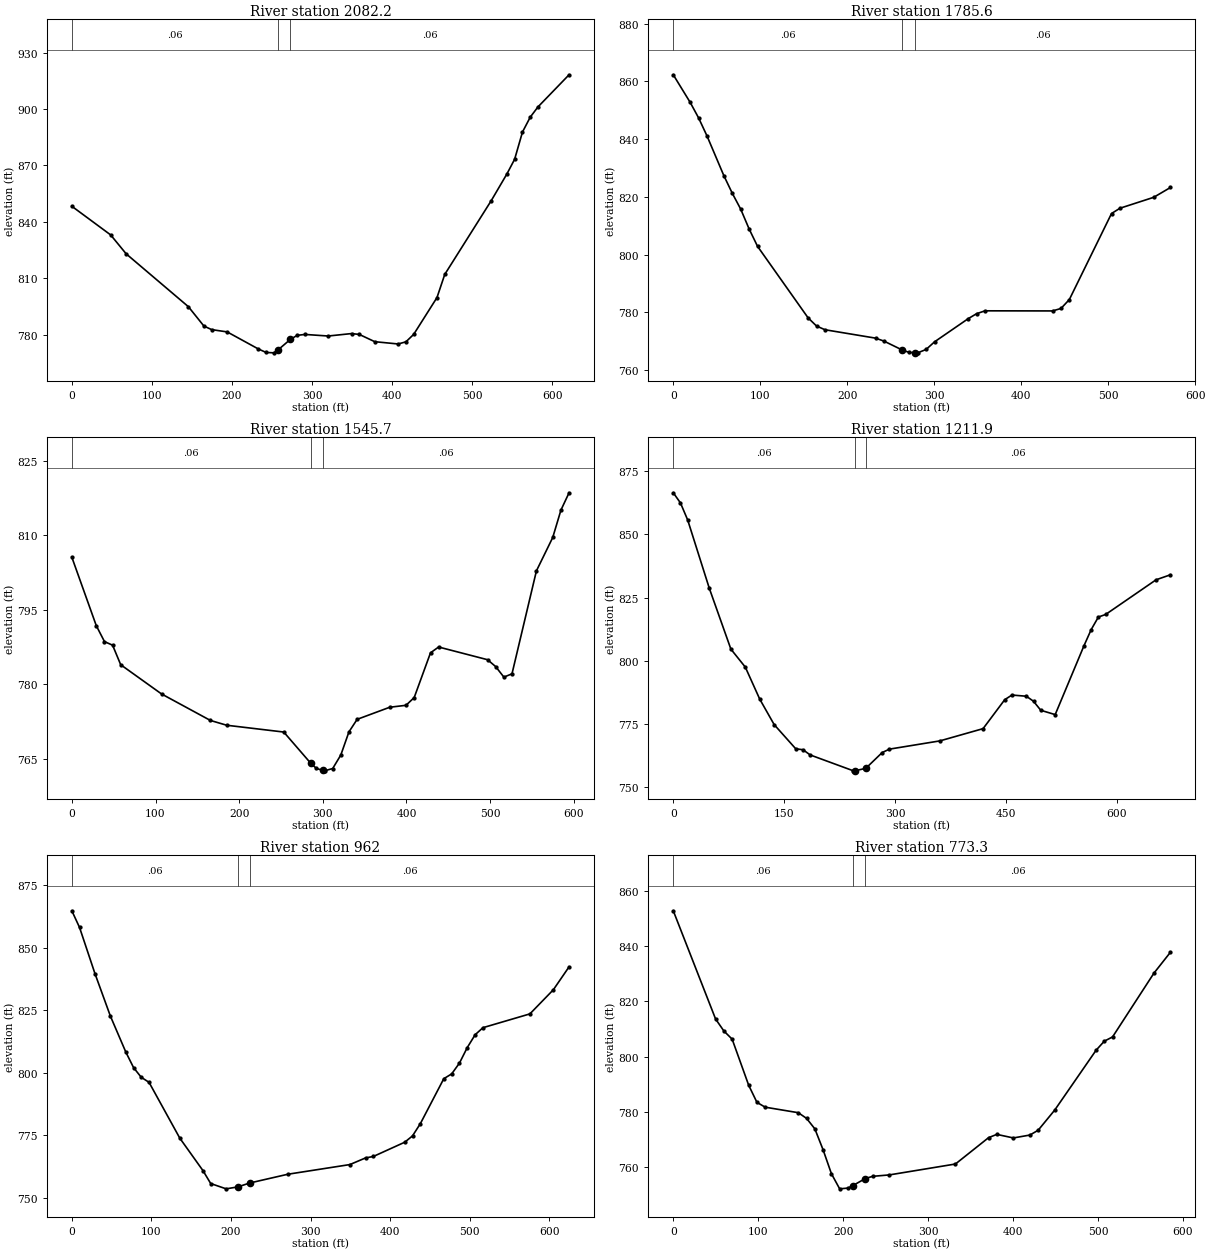
Type RM Length L Ch R = 1 ,2082.2  ,296.4,296.4,296.5
XS GIS Cut Line= 2
     1724952.868      247457.832     1724390.414      247721.522
#Sta/Elev= 30
       0  848.31    48.5  833.08    67.9  823.02   145.6  794.94     165  784.65
   174.7  782.75   194.1  781.53     233  772.47   242.7  770.62   252.4  770.41
   257.9  772.07   272.9  777.52   281.5   779.7   291.2  780.19   320.3  779.35
   349.4  780.65   359.1   780.2   378.5  776.33   407.7  775.12   417.4  776.27
   427.1  780.23   456.2  799.79   465.9  812.09   524.1  851.37   543.6  865.52
   553.2  873.29     563  887.76   572.7  895.67   582.4  901.13   621.2  918.19
#Mann= 3 , 0 , 0
       0     .06       0   257.9    .045       0   272.9     .06       0
#XS Ineff= 2 , 0
                          349.69           780.3
Permanent Ineff=
       F       F
Bank Sta=257.9,272.9
XS Rating Curve= 0 ,0
Exp/Cntr=0.3,0.1

Type RM Length L Ch R = 1 ,1785.6  ,253.6,239.9,226.1
XS GIS Cut Line= 2
     1724859.854      247178.674     1724342.188      247421.366
#Sta/Elev= 30
       0  862.27    19.4  852.73    29.1  847.35    38.8  841.08    58.1  827.38
    67.8  821.27    77.5  815.77    87.2  808.89    96.9  802.86     155  778.11
   164.7  775.28   174.4  773.99   232.6  771.08   242.3  770.05   263.2  766.98
   271.3  766.13   278.2  766.03     281  765.99   290.7  767.16   300.4   769.8
   339.2  777.84   348.8  779.55   358.5  780.54   436.1   780.5   445.8  781.36
   455.4  784.44   503.9  814.23   513.6  816.06   552.4  819.84   571.7  823.25
#Mann= 3 , 0 , 0
       0     .06       0   263.2    .045       0   278.2     .06       0
Bank Sta=263.2,278.2
XS Rating Curve= 0 ,0
Exp/Cntr=0.3,0.1

Type RM Length L Ch R = 1 ,1545.7  ,350.8,333.7,316.6
XS GIS Cut Line= 2
     1724606.932      246858.169     1724308.937      247372.348
#Sta/Elev= 30
       0  805.58    29.2  791.79      39  788.57    48.7  787.85    58.4  783.91
   107.2  778.02   165.6  772.68   185.1  771.71   253.3  770.34   285.6  764.04
   292.3     763   300.6  762.59     302  762.52   311.8  762.99   321.5  765.71
   331.2  770.37     341   772.9     380  775.34   399.4  775.73   409.2  777.29
   428.7  786.31   438.4  787.48   496.9  784.92   506.6  783.53   516.4  781.41
   526.1  782.08   555.3  802.83   574.8  809.56   584.6  815.08   594.3  818.57
#Mann= 3 , 0 , 0
       0     .06       0   285.6    .045       0   300.6     .06       0
Bank Sta=285.6,300.6
XS Rating Curve= 0 ,0
Exp/Cntr=0.3,0.1

Type RM Length L Ch R = 1 ,1211.9  ,256.3,249.8,243.3
XS GIS Cut Line= 2
     1724084.832      246778.493      1724231.54      247434.546
#Sta/Elev= 30
       0   866.5     9.7  862.49    19.5  855.73    48.7  828.72    77.9  804.64
    97.4  797.52   116.9  784.86   136.4  774.78   165.6   765.2   175.4  764.83
   185.1  762.77   243.6  756.48   245.3  756.48   260.3  757.47   282.5  763.72
   292.3  765.07   360.5  768.33   418.9  773.18   448.2  784.64   457.9  786.47
   477.4     786   487.1  784.01   496.9  780.44   516.4  778.73   555.3  805.96
   565.1  812.38   574.8  817.34   584.6  818.35   652.8  832.07   672.3  834.06
#Mann= 3 , 0 , 0
       0     .06       0   245.3    .045       0   260.3     .06       0
Bank Sta=245.3,260.3
XS Rating Curve= 0 ,0
Exp/Cntr=0.3,0.1

Type RM Length L Ch R = 1 ,962     ,186.2,188.8,191.3
XS GIS Cut Line= 3
     1723810.199      246924.951     1723969.606      247202.343
     1724121.495      247466.654
#Sta/Elev= 30
       0  864.75     9.7  858.07    29.1   839.6    48.5  822.61    67.9  808.23
    77.6  802.05    87.2  798.21      97  796.19   135.7  773.86   164.8  760.89
   174.5  755.74   193.9  753.62   208.5  754.39   223.5  755.95   271.5  759.46
   349.4  763.32   369.1  765.98   378.9  766.56   418.3  772.25   428.1  774.79
   437.9  779.65   467.4  797.64   477.3  799.56   487.1  803.89   496.9  810.09
   506.8  815.21   516.6  818.03   575.6  823.54   605.1   833.2   624.8  842.34
#Mann= 3 , 0 , 0
       0     .06       0   208.5    .045       0   223.5     .06       0
Bank Sta=208.5,223.5
XS Rating Curve= 0 ,0
Exp/Cntr=0.3,0.1

Type RM Length L Ch R = 1 ,773.3   ,233.8,235.8,237.9
XS GIS Cut Line= 3
     1723675.625      247015.986     1723679.917      247025.976
     1723906.688      247553.861
#Sta/Elev= 30
       0  852.79    49.8  813.61    59.6  809.25    69.3  806.31    88.8   789.6
    98.5  783.42   108.2  781.67   147.2  779.67   156.9  777.62   166.7  773.82
   176.4  766.23   186.2  757.57   195.9   752.1   205.6  752.37   211.2  753.24
   226.2  755.84   234.8  756.63   254.3  757.14   332.2  761.09   371.2  770.63
   380.9  771.82   400.4  770.53   419.9  771.58   429.6  773.32   449.1  780.62
   497.8  802.29   507.5  805.58   517.2  807.11   565.9   830.2   585.4   837.8
#Mann= 3 , 0 , 0
       0     .06       0   211.2    .045       0   226.2     .06       0
Bank Sta=211.2,226.2
XS Rating Curve= 0 ,0
Exp/Cntr=0.3,0.1

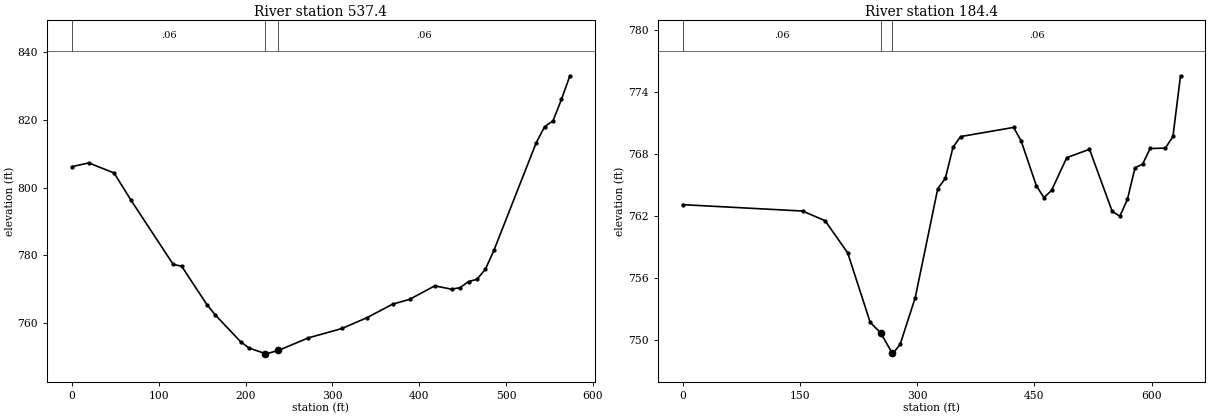
Type RM Length L Ch R = 1 ,537.4   ,338.1,352.8,367.5
XS GIS Cut Line= 2
     1723480.013      247101.801     1723656.928      247647.438
#Sta/Elev= 30
       0  806.21    19.4  807.32    48.6  804.34      68  796.32   116.7  777.28
   126.4  776.76   155.6  765.36   165.3   762.3   194.4  754.39   204.2  752.51
   222.7  750.91   223.6  750.82   237.7  751.81   272.2  755.53   311.1  758.32
   340.3  761.57   369.4  765.52   388.9  766.93     418  770.94   437.5  769.93
   447.2  770.42   456.9   772.2   466.7   772.9   476.4  775.92   486.1  781.44
   534.7  813.21   544.4     818   554.2  819.79   563.9   826.1   573.6   833.1
#Mann= 3 , 0 , 0
       0     .06       0   222.7    .045       0   237.7     .06       0
Bank Sta=222.7,237.7
XS Rating Curve= 0 ,0
Exp/Cntr=0.3,0.1

Type RM Length L Ch R = 1 ,184.4   ,194.5,184.3,174.2
XS GIS Cut Line= 3
     1723314.515      247124.786     1723207.557       247433.16
      1723285.69       247733.54
#Sta/Elev= 30
       0  763.13   153.6  762.51   182.4  761.57   211.2  758.46     240  751.73
   253.3  750.72   268.3  748.72   268.8  748.68   278.4  749.62   297.6  754.13
   326.4  764.68   336.1  765.68   345.8  768.67   355.5  769.72   423.4  770.61
   433.1  769.28   452.5  764.95   462.2  763.81   471.9  764.51   491.3  767.68
   520.4  768.49   549.5  762.47   559.2  762.01   568.9  763.63   578.6   766.7
   588.3  767.05     598  768.57   617.4   768.6   627.1  769.73   636.8  775.61
#Mann= 3 , 0 , 0
       0     .06       0   253.3    .045       0   268.3     .06       0
Bank Sta=253.3,268.3
XS Rating Curve= 0 ,0
Exp/Cntr=0.3,0.1

Chan Stop Cuts=-1
Use User Specified Reach Order=0
Composite Channel Slope=5